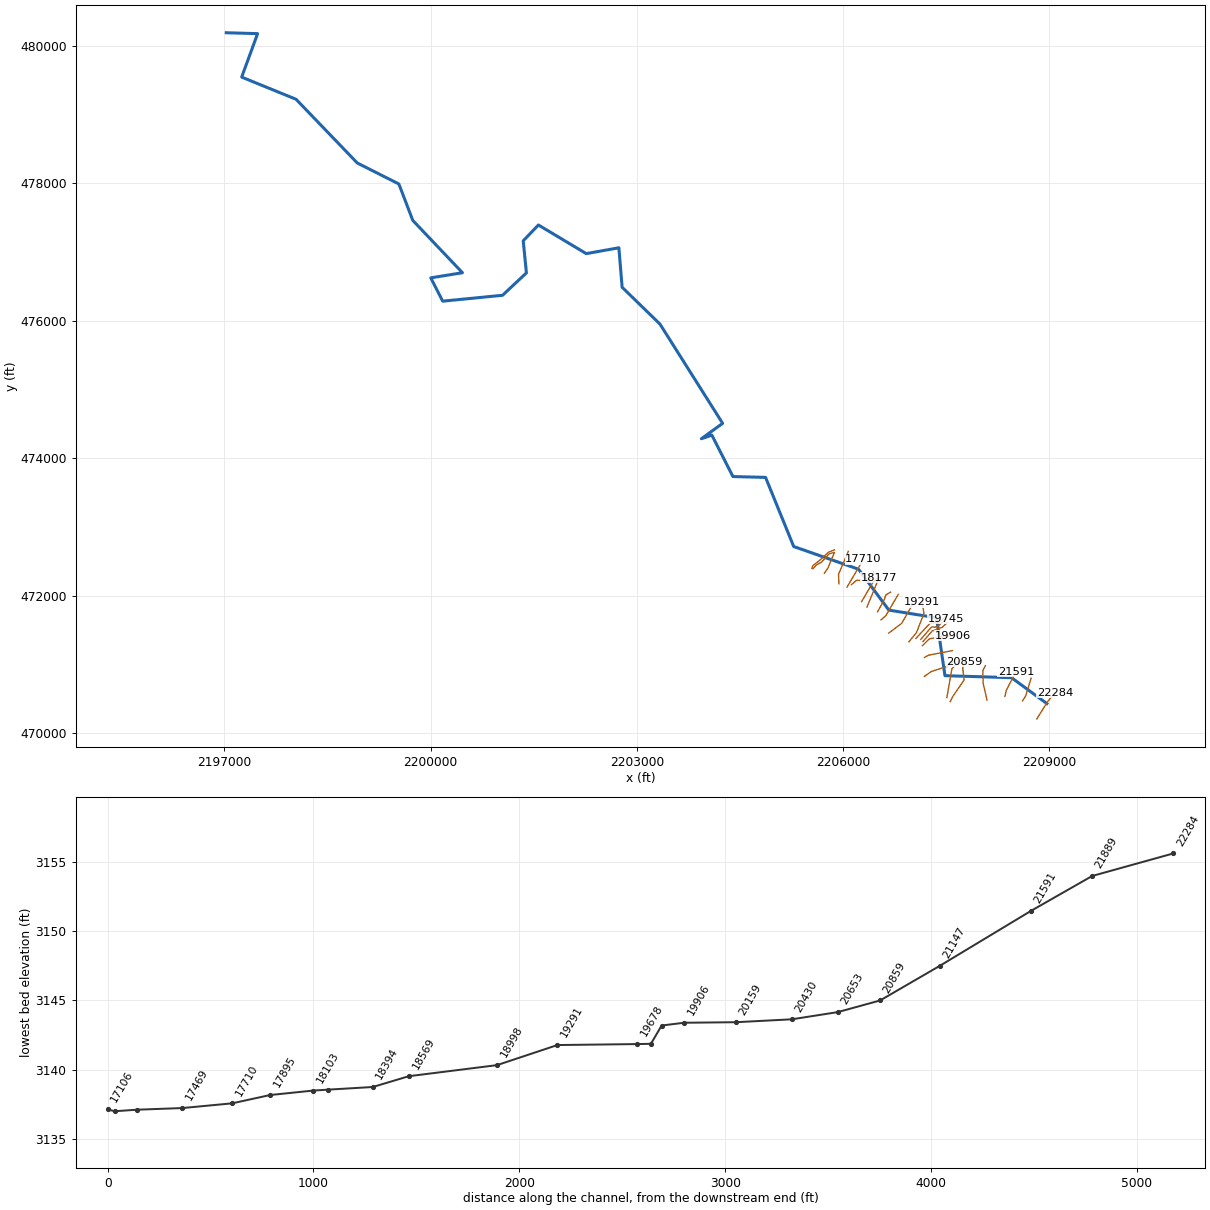
--- BIGLAURLCK.prj (project) ---

Proj Title=BIGLAURLCK
Current Plan=p01
Default Exp/Contr=0,0
English Units
Geom File=g01
Flow File=f01
Plan File=p01
Background Map Layer=Inundation Boundary (01pct Value_0)
BEGIN DESCRIPTION:
----------MODEL BY WOOD PLC 2021----------
Stream Name: Big Laurel Creek
Flood Zone: Approximate
Pocahontas County, WV
HEC-RAS Version: RAS 6.1
Vertical Datum: NAVD88
Projection: NAD 1983 StatePlane West Virginia S FIPS 4702 (US Feet)
Terrain: 1-meter LIDAR (FEMA Region III 3DEP collected 2016-2018)
Land Use: 2016 NLCD
Hydrologic Method:
WV 2010 Regional Regression Equations
Model Notes:
Model ties in to WILLIAMSRV at the downstream
END DESCRIPTION:
DSS File=dss
DSS Export Rating Curves= 0
DSS Export Rating Curve Sorted= 0
DSS Export Volume Flow Curves= 0
DXF OffsetX= 0
DXF OffsetY= 0
DXF ScaleX= 0
DXF ScaleY= 0

--- BIGLAURLCK.p01 (plan) ---

Plan Title=Floodplain
Program Version=6.10
Short Identifier=Floodplain
Geom File=g01
Flow File=f01
Subcritical Flow
K Sum by GR= 0
Std Step Tol= 0.01
Critical Tol= 0.01
Num of Std Step Trials= 20
Max Error Tol= 0.3
Flow Tol Ratio= 0.001
Split Flow NTrial= 30
Split Flow Tol= 0.02
Split Flow Ratio= 0.02
Log Output Level= 0
Friction Slope Method= 1
Unsteady Friction Slope Method= 2
Unsteady Bridges Friction Slope Method= 1
Parabolic Critical Depth
Global Vel Dist= 0 , 0 , 0
Global Log Level= 0
CheckData=True
Encroach Param=-1 ,0,0, 0
Computation Interval=0.1SEC
Output Interval=1SEC
Instantaneous Interval=Max Profile
Mapping Interval=1HOUR
Computation Time Step Use Courant=        0
Computation Time Step Use Time Series=    0
Computation Time Step Count To Double=0
Computation Time Step Max Doubling=0
Computation Time Step Max Halving=0
Computation Time Step Residence Courant=0
Run HTab= 0
Run UNet= 0
Run Sediment= 0
Run PostProcess= 0
Run WQNet= 0
Run RASMapper=-1
UNET Theta= 0
UNET Theta Warmup= 0
UNET ZTol= 0
UNET ZSATol= 0
UNET MxIter= 0
UNET Max Iter WO Improvement= 0
UNET MaxInSteps= 0
UNET DtIC= 0
UNET DtMin= 0
UNET MaxCRTS= 0
UNET WFStab= 0
UNET SFStab= 0
UNET WFX= 1
UNET SFX= 1
UNET Gravity=32.174
UNET 1D Methodology=Finite Difference
UNET DSS MLevel= 1
UNET Pardiso=0
UNET DZMax Abort= 0
UNET Use Existing IB Tables= 0
UNET Froude Reduction=False
UNET Froude Limit= 0
UNET Froude Power= 0
UNET D1 Cores= 0
UNET WindReference=Eulerian
UNET WindDragFormulation=Hsu (1988)
UNET D2 Coriolis=0
UNET D2 Cores= 0
UNET D2 Theta= 1
UNET D2 Theta Warmup= 1
UNET D2 Z Tol= 0.01
UNET D2 Volume Tol= 0.01
UNET D2 Max Iterations= 20
UNET D2 Equation= 0
UNET D2 RampUpFraction=0.1
UNET D2 TimeSlices= 1
UNET D2 Turbulence Formulation=Non-Conservative (original)
UNET D2 Eddy Viscosity=0.3
UNET D2 Transverse Eddy Viscosity=0.1
UNET D2 Smagorinsky Mixing=0
UNET D2 BCVolumeCheck=0
UNET D2 Cores=0
UNET D2 SolverType=PARDISO (Direct)
UNET D2 Minimum Iterations= 2147483647
UNET D2 Maximum Iterations= 2147483647
UNET D2 Restart Number= 10
UNET D2 Relaxation Coeff=1.3
UNET D2 SOR Precondition Iterations= 10
UNET D2 ILUT Maximum Fill= 8
UNET D2 ILUT Tolerance=1E-08
UNET D1D2 MaxIter= 0
UNET D1D2 ZTol=0.01
UNET D1D2 QTol=0.1
UNET D1D2 MinQTol=1
DSS File=dss
Write IC File= 0
Write IC File at Fixed DateTime=0
Write IC File at Sim End=0
Echo Input=False
Echo Parameters=False
Echo Output=False
Write Detailed= 0
HDF Write Warmup=0
HDF Write Time Slices=0
HDF Flush=0
HDF Compression= 1
HDF Chunk Size= 1
HDF Spatial Parts= 1
HDF Use Max Rows=0
HDF Fixed Rows= 1
Calibration Method= 0
Calibration Iterations= 20
Calibration Max Change=0.05
Calibration Tolerance=0.2
Calibration Maximum=1.5
Calibration Minimum=0.5
Calibration Optimization Method= 1
WQ AD Non Conservative
WQ ULTIMATE=-1
WQ Max Comp Step=1HOUR
WQ Output Interval=15MIN
WQ Output Selected Increments= 0
WQ Output face flow=0
WQ Output face velocity=0
WQ Output face area=0
WQ Output face dispersion=0
WQ Output cell volume=0
WQ Output cell surface area=0
WQ Output cell continuity=0
WQ Output cumulative cell continuity=0
WQ Output face conc=0
WQ Output face dconc_dx=0
WQ Output face courant=0
WQ Output face peclet=0
WQ Output face adv mass=0
WQ Output face disp mass=0
WQ Output cell mass=0
WQ Output cell source sink temp=0
WQ Output nsm pathways=0
WQ Output nsm derived pathways=0
WQ Create Restart=0
WQ Fixed Restart=0
WQ System Summary=0
WQ Write To DSS=0
Sorting and Armoring Iterations= 10
XS Update Threshold= 0.02
Bed Roughness Predictor= 0
Hydraulics Update Threshold= 0.02
Energy Slope Method= 1
Volume Change Method= 1
Sediment Retention Method= 0
Sediment TS Multiplier= 1
Warm Up Method= 0
XS Weighting Method= 0
Number of US Weighted Cross Sections= 1
Number of DS Weighted Cross Sections= 1
Upstream XS Weight=0
Main XS Weight=1
Downstream XS Weight=0
Number of DS XS's Weighted with US Boundary= 1
Upstream Boundary Weight= 1
Weight of XSs Associated with US Boundary= 0
Number of US XS's Weighted with DS Boundary= 1
Downstream Boundary Weight= 0.5
Weight of XSs Associated with DS Boundary= 0.5
Percentile Method= 0
Sediment Output Level= 3
Mass or Volume Output= 0
Output Increment Type= 1
Profile and TS Output Increment= 1
Transport Output Increment 1
XS Output Flag= 0
XS Output Increment= 10
Read HDF5 Sediment Hotstart= 0
Sediment Hotstart Type= 0
Write Gradation File= 0
Read Gradation Hotstart= 0
Write HDF5 File= 1
Write Binary Output= 1
Write DSS Sediment File= 0
DSS Sediment Output Type= 1
SV Curve= 0
Specific Gage Flag= 0
Subcell Erosion Methods= 0
Subcell Deposition Methods= 0
Advection Scheme= 1
Matrix Solver= 0
Implicit Weighting Factor= 1
Maximum Outer Loop Convergence Iterations= 5
Convergence Maximum Absolute= 0.001
Convergence RMSE= 0.0001
Grain Fractions Max Abs Error= 0.001
Max Subgrid Regions= 1
Max Subgrid Length Scale= 3.402823E+38
Initial Layer Thickness= 3.402823E+38
Min Layer Thickness= 3.402823E+38
Max Layer Thickness= 3.402823E+38
Number of Layers= 5

--- BIGLAURLCK.f01 (steady flow) ---

Flow Title=Flow
Program Version=6.10
Number of Profiles= 6
Profile Names=01pct,10pct,04pct,02pct,0_2pct,01plus
River Rch & RM=BIGLAURLCK,Main            ,22284
     647     344     456     549     902     957
River Rch & RM=BIGLAURLCK,Main            ,19291
     779     417     551     662    1080    1150
River Rch & RM=BIGLAURLCK,Main            ,16111
    1140     617     810     968    1570    1680
River Rch & RM=BIGLAURLCK,Main            ,16027
    1290     703     921    1100    1770    1910
River Rch & RM=BIGLAURLCK,Main            ,14647
    1450     793    1040    1240    1990    2140
River Rch & RM=BIGLAURLCK,Main            ,7309
    1630     895    1170    1390    2230    2400
Boundary for River Rch & Prof#=BIGLAURLCK,Main            , 1
Up Type= 0
Dn Type= 3
Dn Slope=0.00929
Boundary for River Rch & Prof#=BIGLAURLCK,Main            , 2
Up Type= 0
Dn Type= 3
Dn Slope=0.00929
Boundary for River Rch & Prof#=BIGLAURLCK,Main            , 3
Up Type= 0
Dn Type= 3
Dn Slope=0.00929
Boundary for River Rch & Prof#=BIGLAURLCK,Main            , 4
Up Type= 0
Dn Type= 3
Dn Slope=0.00929
Boundary for River Rch & Prof#=BIGLAURLCK,Main            , 5
Up Type= 0
Dn Type= 3
Dn Slope=0.00929
Boundary for River Rch & Prof#=BIGLAURLCK,Main            , 6
Up Type= 0
Dn Type= 3
Dn Slope=0.00929
DSS Import GetInterval= 0
DSS Import GetPeak= 0
DSS Import FillOption= 0

--- BIGLAURLCK.g01 (geometry) ---

Geom Title=Geometry
Program Version=6.10

River Reach=BIGLAURLCK      ,Main
Reach XY= 30
2208962.92999999470430.3890000132208448.83064929 470807.04608792
2207480.45700003470836.647000015     2207357.425471679.252000004
2206664.17600001471790.1019999982206223.43300004472385.107999995
2205280.21500002 472715.218000012204870.94700001473720.761999995
2204396.24100001 473733.049000012204089.58299999474335.533999994
2203936.87300004474282.8190000062204246.40100004474506.700000003
2203335.09148651475950.6100270192202784.22139766476486.546124007
2202737.33702705477060.5434325032202262.49731294476975.562735529
     2201566.705477392.1519999952201345.89099999477162.038000003
 2201392.3184865476695.1692027352201044.95599999476369.606000006
     2200174.362476284.2390000082200001.19199999476623.204000011
2200461.91400002476697.8400000182199739.45900001477458.457000002
2199537.07800002477988.8110000042198931.95500003         478294.
     2198041.413 479220.865000012197250.45500003479543.279000014
2197482.20700003480175.5330000072197026.70625107 480188.52853024

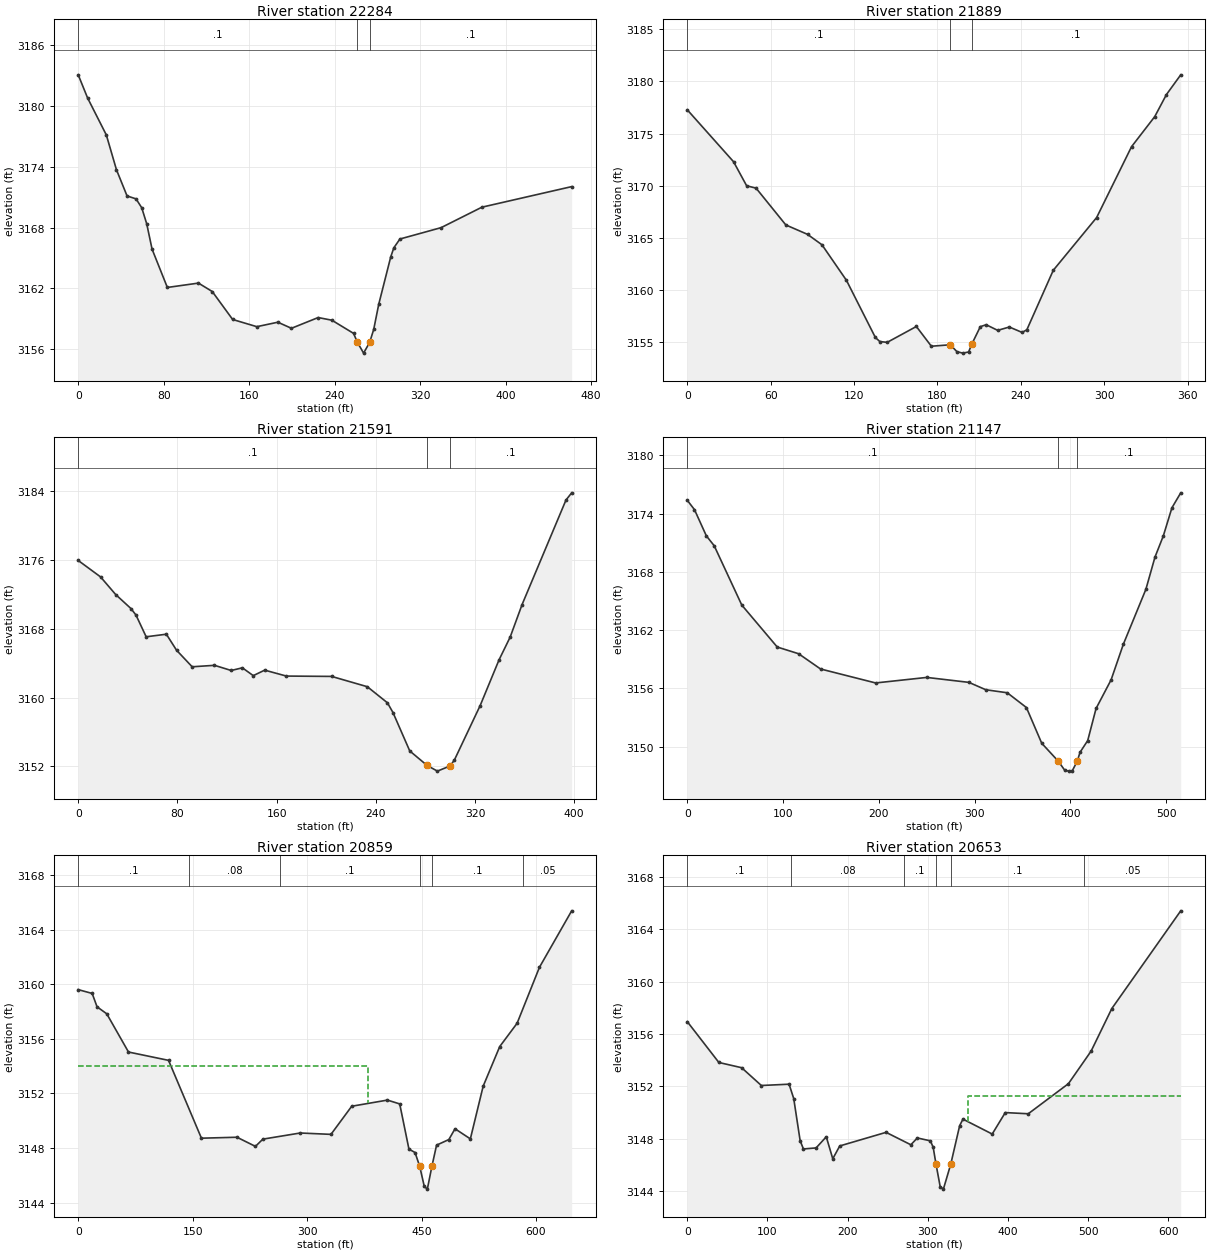
Type RM Length L Ch R = 1 ,22284   ,389.8,394.8,400
XS GIS Cut Line= 3
2208815.48138797470206.8586093782208972.77351341470458.087641556
2209077.90386842470585.689794484
#Sta/Elev= 30
       0 3183.07     8.8 3180.78    26.3 3177.14    35.8  3173.7    45.7 3171.12
    54.1 3170.83    59.4 3169.96    64.1 3168.37    69.1 3165.87    83.4 3162.09
   112.5 3162.52   125.4 3161.69   144.5 3158.93   167.1 3158.22   186.8 3158.66
   199.5 3158.06   224.5 3159.12   237.3 3158.86   257.6 3157.56  261.22 3156.68
     267 3155.61   272.7 3156.67   276.5 3157.96   281.2 3160.44   292.4  3165.1
   295.3    3166     301 3166.87   339.5 3167.99   377.7 3170.01   461.7 3172.04
#Mann= 3 ,-1,0
       0      .1       0  261.22    .045       0   272.7      .1       0
Bank Sta=261.22,272.7
XS Rating Curve= 0 ,0
Exp/Cntr(USF)=0,0
Exp/Cntr=0.3,0.1

Type RM Length L Ch R = 1 ,21889   ,299.5,298.4,291.9
XS GIS Cut Line= 3
2208608.30838929 470468.914632232208653.94450606470542.380976059
2208732.94735448470798.959975838
#Sta/Elev= 30
       0 3177.27    33.3  3172.3    42.7    3170    49.5 3169.77    70.9 3166.25
    86.5 3165.35    96.9 3164.35   114.5 3160.95   135.3 3155.48   138.5 3155.09
   143.8 3155.01   164.8 3156.53   175.6 3154.64   189.2 3154.78     194 3154.12
   198.2 3153.98   202.4 3154.09  204.65 3154.83   210.8 3156.51     215  3156.7
   223.3 3156.16   231.7 3156.48   240.9 3155.96   244.3 3156.22   263.3 3161.91
   294.5 3166.96   319.6 3173.74   336.3 3176.62   344.7 3178.73     355 3180.62
#Mann= 3 ,-1,0
       0      .1       0   189.2    .045       0  204.65      .1       0
Bank Sta=189.2,204.65
XS Rating Curve= 0 ,0
Exp/Cntr(USF)=0,0
Exp/Cntr=0.3,0.1

Type RM Length L Ch R = 1 ,21591   ,434.1,443.2,452.9
XS GIS Cut Line= 3
2208353.68067992470535.6125606222208371.99191088470621.543730153
2208513.95319802470897.230285495
#Sta/Elev= 30
       0 3175.96      18 3174.05    30.2    3172    42.5 3170.37    46.6 3169.61
    54.8 3167.08    71.1 3167.38    79.3 3165.52    91.9 3163.59   109.9 3163.76
   123.4 3163.16   132.4 3163.47   141.2 3162.56   150.4  3163.2   167.9 3162.51
   204.4 3162.47   233.2 3161.27   249.4  3159.4   253.9 3158.26   267.4  3153.8
   281.4 3152.11   289.7 3151.45   299.9 3152.05   303.4 3152.74   324.2 3159.08
   339.4 3164.39   348.4 3167.05     358 3170.83   393.4 3182.99     398 3183.83
#Mann= 3 ,-1,0
       0      .1       0   281.4    .045       0   299.9      .1       0
Bank Sta=281.4,299.9
XS Rating Curve= 0 ,0
Exp/Cntr(USF)=0,0
Exp/Cntr=0.3,0.1

Type RM Length L Ch R = 1 ,21147   ,286.7,288.8,290.2
XS GIS Cut Line= 4
2208092.61464541470481.8333199942208035.44334265470724.068737556
2208032.68949002470914.5741108832208068.46742524470981.211488379
#Sta/Elev= 30
       0 3175.37     7.5 3174.41    19.9 3171.71    28.1 3170.69    56.9 3164.58
    93.9 3160.26   116.2 3159.57   139.1    3158   196.6 3156.56     250 3157.13
     294 3156.62   311.6 3155.86     334 3155.55     354 3154.03     370 3150.35
   387.3  3148.5     394 3147.57     398 3147.48     402 3147.54     407 3148.49
     410 3149.42     418 3150.63   426.7 3153.93   442.4 3156.88   455.2 3160.55
   478.7  3166.2   488.2 3169.52   496.9  3171.7   505.9  3174.6   515.1 3176.14
#Mann= 3 ,-1,0
       0      .1       0   387.3    .045       0     407      .1       0
Bank Sta=387.3,407
XS Rating Curve= 0 ,0
Exp/Cntr(USF)=0,0
Exp/Cntr=0.3,0.1

Type RM Length L Ch R = 1 ,20859   ,210.1,205.3,199.7
XS GIS Cut Line= 5
2207557.09826697470459.7625628012207595.08107777470535.644306793
2207758.45348997 470773.35116655 2207738.3785416470951.923338519
2207766.30062139471041.495918049
#Sta/Elev= 30
       0  3159.6    18.3 3159.32    24.7 3158.34    37.4 3157.83    65.9 3155.03
   118.4 3154.42   161.5 3148.72   208.1 3148.79   232.3 3148.12     242 3148.65
     291  3149.1   331.3    3149   358.5 3151.06   405.3 3151.51   421.4 3151.23
   433.5 3147.92   441.5 3147.67   447.6 3146.66   453.6 3145.19   457.6 3144.99
  463.75  3146.7   469.7 3148.21   485.8 3148.62   493.9 3149.41     514 3148.67
   530.8 3152.53   552.5 3155.43   575.3 3157.14   604.6 3161.24   646.8 3165.37
#Mann= 6 ,-1,0
       0      .1       0  144.86     .08       0  264.86      .1       0
   447.6    .045       0  463.75      .1       0  582.99     .05       0
#XS Ineff= 2 , 0
          379.38 3154.02
Permanent Ineff=
       F       F
Bank Sta=447.6,463.75
XS Rating Curve= 0 ,0
Exp/Cntr(USF)=0,0
Exp/Cntr=0.3,0.1

Type RM Length L Ch R = 1 ,20653   ,243,223.3,202.2
XS GIS Cut Line= 3
 2207508.1135986470518.3900289562207581.06230943470937.443672989
 2207718.1552659 471069.29221956
#Sta/Elev= 30
       0 3156.95    39.4 3153.83    67.8 3153.43    92.4 3152.07     127 3152.17
   132.8 3151.07   140.8 3147.85   144.9 3147.22   160.7  3147.3   173.4 3148.15
   181.5 3146.47   190.2 3147.45     248 3148.49   278.9 3147.54     287 3148.06
   303.3 3147.84   306.8 3147.34   310.2 3146.09   315.5 3144.34   319.5 3144.15
   328.7 3146.06   339.8    3149   343.9  3149.5   380.4 3148.36   396.7    3150
   425.4 3149.91   475.5 3152.21   503.8  3154.7   529.6 3157.95   615.6 3165.42
#Mann= 6 ,-1,0
       0      .1       0     130     .08       0     270      .1       0
   310.2    .045       0   328.7      .1       0  495.36     .05       0
#XS Ineff= 2 , 0
                           350.2         3151.27
Permanent Ineff=
       F       F
Bank Sta=310.2,328.7
XS Rating Curve= 0 ,0
Exp/Cntr(USF)=0,0
Exp/Cntr=0.3,0.1

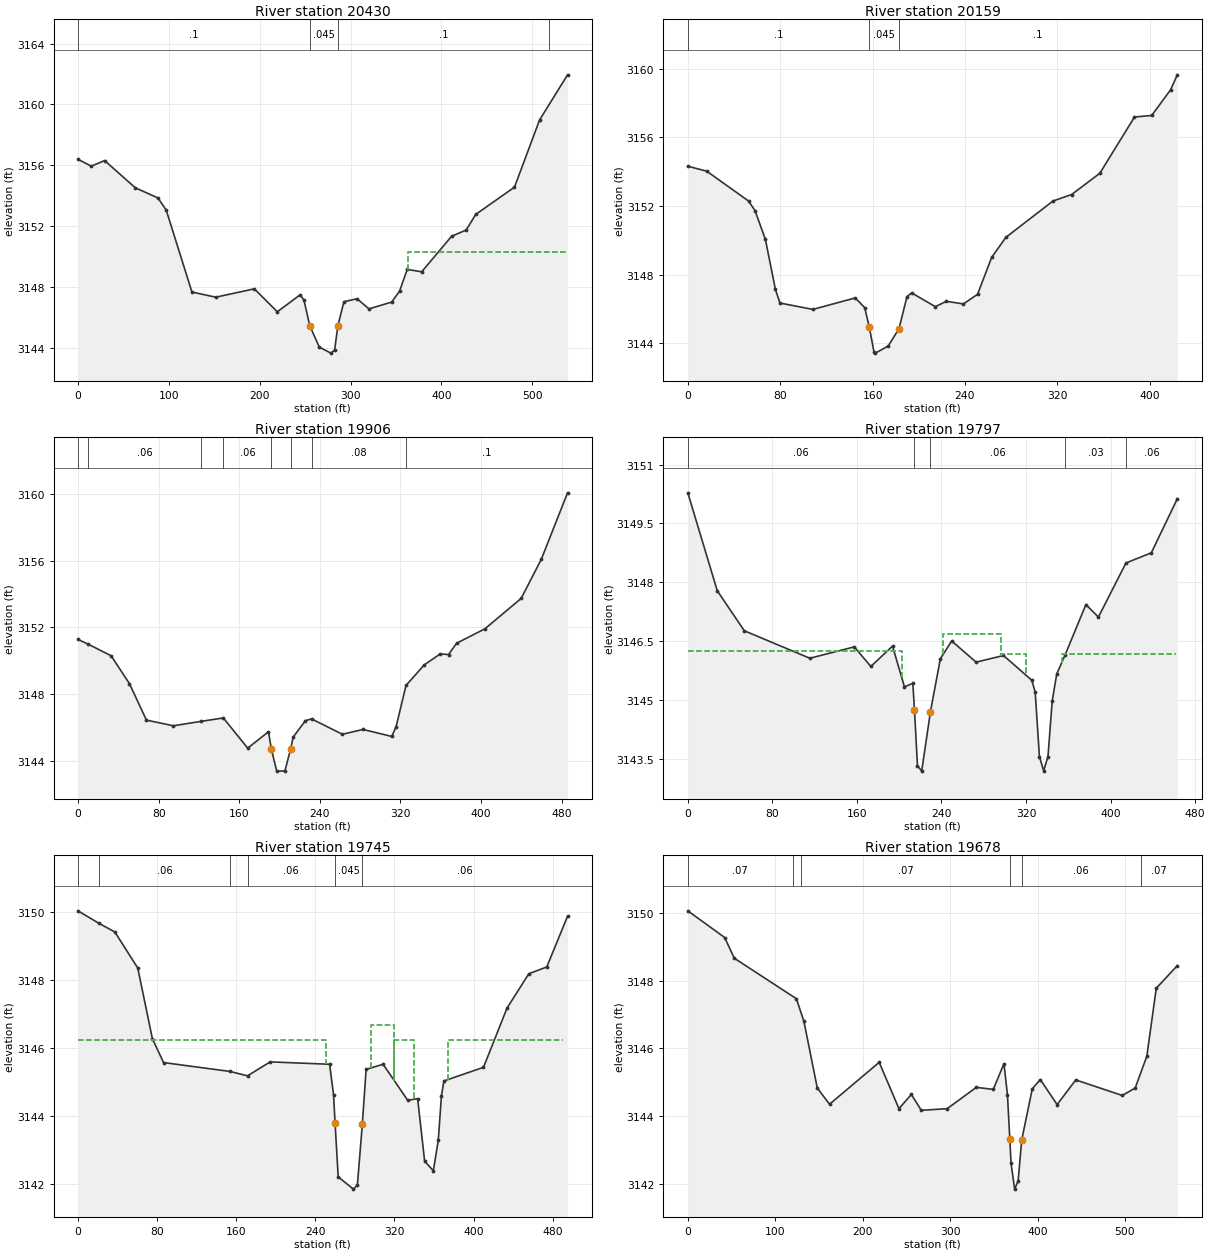
Type RM Length L Ch R = 1 ,20430   ,268.7,270.7,263.4
XS GIS Cut Line= 4
2207180.19258036 470825.389201042207282.84389001470897.497404594
2207523.33755806470975.6118908112207644.06965668471081.451086331
#Sta/Elev= 30
       0 3156.38    14.6 3155.93    29.3  3156.3      63 3154.51      88 3153.84
    97.1 3153.04   125.4 3147.65   151.6 3147.31   194.1 3147.86   219.4 3146.35
   244.6 3147.47   248.8  3147.1  255.12 3145.43   265.6 3144.03   278.3 3143.63
   282.5 3143.83  285.98 3145.41   292.7 3147.01   307.2 3147.21   320.3 3146.54
   345.3 3146.99     354 3147.71   362.4 3149.14   378.3 3148.98   411.3 3151.32
   427.3 3151.73   437.9 3152.76   480.5 3154.55   508.1 3158.97   538.9 3161.94
#Mann= 4 ,-1,0
       0      .1       0  255.12    .045       0  285.98      .1       0
  518.31     .05       0
#XS Ineff= 2 , 0
                          363.72          3150.3
Permanent Ineff=
       F       F
Bank Sta=255.12,285.98
XS Rating Curve= 0 ,0
Exp/Cntr(USF)=0,0
Exp/Cntr=0.3,0.1

Type RM Length L Ch R = 1 ,20159   ,250.7,253.1,249.9
XS GIS Cut Line= 3
2207180.75549669471101.5350168562207243.75504599471134.816074423
2207589.99445528471201.652951412
#Sta/Elev= 30
       0 3154.32    16.4 3154.03    52.6 3152.29    58.2 3151.73    67.2 3150.05
    75.8 3147.15    79.8 3146.34   108.3 3145.97     145 3146.64   153.2 3146.07
   157.2 3144.92   161.3 3143.46   162.4 3143.42   173.5 3143.83   182.9 3144.85
   189.8 3146.72   193.9 3146.93   214.3 3146.13   223.9 3146.44   238.7 3146.29
   250.9 3146.85   263.1    3149   275.4 3150.17   316.2 3152.29   332.4 3152.67
   356.8 3153.91   386.8 3157.19   401.7 3157.28     418 3158.77   423.9 3159.65
#Mann= 3 ,-1,0
       0      .1       0   157.2    .045       0   182.9      .1       0
Bank Sta=157.2,182.9
XS Rating Curve= 0 ,0
Exp/Cntr(USF)=0,0
Exp/Cntr=0.3,0.1

Type RM Length L Ch R = 1 ,19906   ,99.4,109,112
BEGIN DESCRIPTION:
xs 4
END DESCRIPTION:
XS GIS Cut Line= 4
2207152.91967172471272.3492175092207252.99618965471371.608590302
2207432.33487513471406.9650511262207594.07402605471416.487528516
#Sta/Elev= 30
       0 3151.28    10.2 3150.99    32.8  3150.3      51 3148.63    67.9 3146.44
    94.7  3146.1   121.7 3146.36   144.2 3146.57   168.4 3144.76     189 3145.74
  191.83 3144.71   197.2 3143.38   205.3 3143.39   211.1 3144.73   213.5 3145.42
   225.7 3146.41   231.8 3146.51   262.4 3145.59   282.8 3145.88   311.3 3145.46
   315.7 3146.05   325.5 3148.52   343.6 3149.75   359.5 3150.41   367.7 3150.37
   375.7 3151.05   403.7 3151.91   439.8 3153.74   459.8 3156.09   485.8 3160.07
#Mann= 8 ,-1,0
       0      .1       0    10.2     .06       0   121.7     .03       0
   144.2     .06       0  191.83    .045       0   211.1     .06       0
   231.8     .08       0   325.5      .1       0
Bank Sta=191.83,211.1
XS Rating Curve= 0 ,0
Exp/Cntr(USF)=0,0
Exp/Cntr=0.5,0.3

Type RM Length L Ch R = 1 ,19797   ,67.2,52.1,49.1
BEGIN DESCRIPTION:
xs 3
END DESCRIPTION:
XS GIS Cut Line= 6
2207160.89802842471333.1002976422207299.73496124471492.298124648
2207312.88520172471492.2981246482207404.93688505471529.672492317
2207440.19924721471539.5403289232207514.26889814471607.853903171
#Sta/Elev= 30
       0 3150.28    27.9 3147.78    53.5 3146.76   115.5 3146.06   157.5 3146.35
   173.2 3145.85   193.7 3146.37     205 3145.33   212.9 3145.42  214.47 3144.75
   217.3 3143.32   221.3 3143.18   229.6  3144.7     239 3146.05   249.7  3146.5
   272.8 3145.96   298.7 3146.13   325.4  3145.5   328.7  3145.2   332.7 3143.55
   336.7 3143.19   340.8 3143.55   344.8 3144.97   349.1 3145.66   357.1 3146.15
   376.7 3147.43   388.5 3147.11   414.6 3148.49   438.6 3148.75   463.2 3150.13
#Mann= 5 ,-1,0
       0     .06       0  214.47    .045       0   229.6     .06       0
   357.1     .03       0   414.6     .06       0
#XS Ineff= 4 ,-1
       0   202.5 3146.25   241.6     296 3146.67     296     320 3146.17
   353.8   461.8 3146.17
Permanent Ineff=
       F       F       F       F
Bank Sta=214.47,229.6
XS Rating Curve= 0 ,0
Exp/Cntr(USF)=0,0
Exp/Cntr=0.5,0.3

Type RM Length L Ch R = 1 ,19745   ,64.8,67.5,66.8
BEGIN DESCRIPTION:
xs 2
END DESCRIPTION:
XS GIS Cut Line= 6
2207127.84063779471363.4591257722207273.56301281471532.119282047
  2207290.891547471546.004092025   2207336.90763 471542.09706611
2207378.80695033471558.4302664252207498.21834097471662.999563316
#Sta/Elev= 30
       0 3150.04    21.3 3149.67    37.2 3149.42    60.4 3148.36    75.2 3146.28
    86.5 3145.58   153.5 3145.32   171.4 3145.19   194.3  3145.6   254.4 3145.53
   258.4 3144.63  259.91 3143.81   263.1 3142.22   278.5 3141.86   282.5 3141.98
   287.53143.771   291.3 3145.38   308.5 3145.53   333.4 3144.47   343.4 3144.52
   350.5 3142.68   359.3  3142.4   364.3  3143.3   367.5 3144.61     370 3145.04
     410 3145.44   433.8 3147.18   455.8 3148.19     474 3148.39     495 3149.88
#Mann= 6 ,-1,0
       0     .03       0    21.3     .06       0   153.5     .07       0
   171.4     .06       0  259.91    .045       0   287.5     .06       0
#XS Ineff= 4 ,-1
       0   250.9 3146.25   296.5     320 3146.67     320     340 3146.25
   373.7   490.1 3146.25
Permanent Ineff=
       F       F       F       F
Bank Sta=259.91,287.5
XS Rating Curve= 0 ,0
Exp/Cntr(USF)=0,0
Exp/Cntr=0.5,0.3

Type RM Length L Ch R = 1 ,19678   ,324,387,395.1
BEGIN DESCRIPTION:
xs 1
END DESCRIPTION:
XS GIS Cut Line= 4
2207057.67801278471378.3012195242207259.39555969471594.860860181
2207399.72080971471617.7986414342207490.12265347471699.430157071
#Sta/Elev= 30
       0 3150.07    42.2 3149.28    53.1 3148.67   124.2 3147.47   132.8  3146.8
   148.1 3144.83   162.1 3144.35   218.9 3145.59   241.5 3144.22   255.7 3144.64
     267 3144.17   296.7 3144.22     330 3144.85   349.4 3144.79   361.6 3145.55
   365.6 3144.63  368.26 3143.33   369.7 3142.61   373.8 3141.84   377.8 3142.08
   381.9 3143.29     394 3144.81   403.2 3145.08   422.4 3144.34   443.7 3145.07
   496.9 3144.61   511.7 3144.83     525 3145.77   535.8 3147.78   559.9 3148.45
#Mann= 6 ,-1,0
       0     .07       0     120     .06       0     130     .07       0
  368.26    .045       0   381.9     .06       0  518.14     .07       0
Bank Sta=368.26,381.9
XS Rating Curve= 0 ,0
Exp/Cntr(USF)=0,0
Exp/Cntr=0.3,0.1

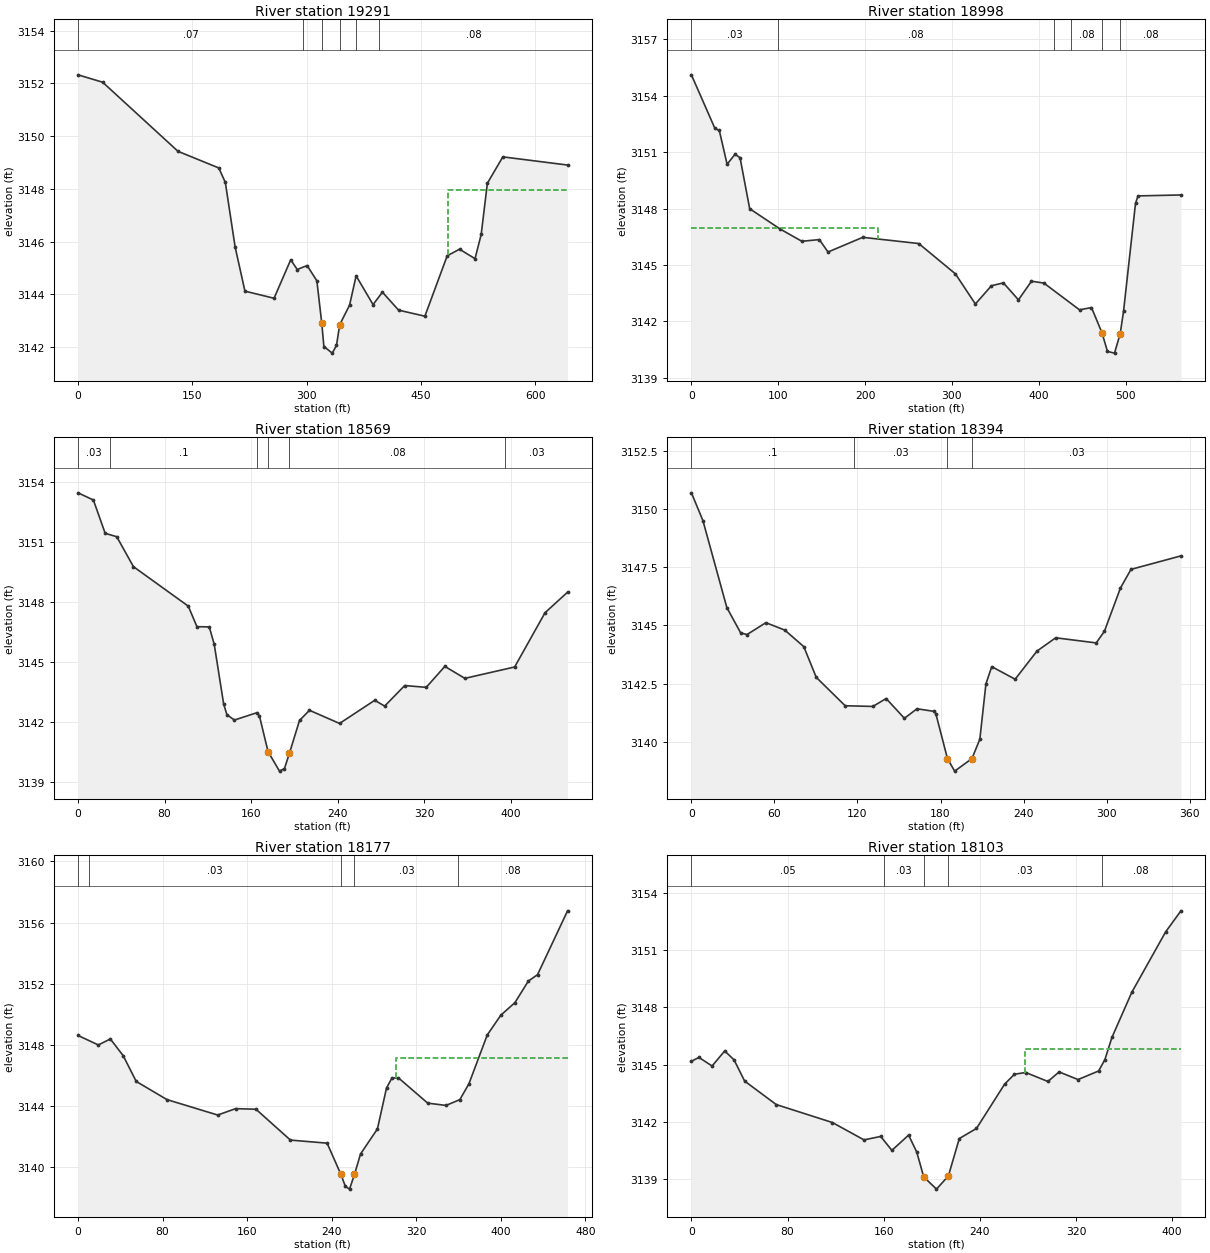
Type RM Length L Ch R = 1 ,19291   ,291.4,292.9,284.6
XS GIS Cut Line= 4
2206955.63670164471329.0171897992207066.93377411 471464.36779193
2207174.96171826471743.0953895022207146.71601467471908.834235958
#Sta/Elev= 30
       0 3152.32    32.3 3152.04   131.2 3149.42   184.7 3148.79   193.3 3148.24
   206.1  3145.8     219 3144.12   257.2 3143.85   279.1 3145.31   287.6 3144.94
   300.6 3145.09   313.4 3144.51  319.83  3142.9   322.6 3142.02   333.6 3141.77
   339.1 3142.06   343.4 3142.85   356.3 3143.59   364.9  3144.7   387.1 3143.61
   399.4 3144.08   420.6  3143.4   455.1 3143.17   484.4 3145.46   500.6 3145.71
   520.9 3145.35     529 3146.27   537.1 3148.21   557.4 3149.21   642.3  3148.9
#Mann= 6 ,-1,0
       0     .07       0  295.23      .1       0  319.83    .045       0
   343.4      .1       0  365.23     .07       0  395.23     .08       0
#XS Ineff= 2 , 0
                          485.67         3147.94
Permanent Ineff=
       F       F
Bank Sta=319.83,343.4
XS Rating Curve= 0 ,0
Exp/Cntr(USF)=0,0
Exp/Cntr=0.3,0.1

Type RM Length L Ch R = 1 ,18998   ,422.2,428.8,423.7
XS GIS Cut Line= 3
2206662.55890304471456.436988746 2206851.8695703 471599.07088367
 2207014.1801607471882.522462494
#Sta/Elev= 30
       0  3155.1    27.1 3152.25    32.1 3152.15    41.1 3150.35    50.2 3150.88
      56  3150.7    67.1 3147.99   102.2 3146.91   127.2 3146.26   147.3 3146.35
   157.3 3145.69   197.3 3146.47   261.8 3146.14     304 3144.53     327 3142.93
   345.5  3143.9   359.3 3144.05   376.6 3143.15   391.6 3144.14   405.9 3144.04
   446.9 3142.62   460.7 3142.74  472.79  3141.4   479.1 3140.41   487.2 3140.32
   493.8 3141.36   497.6 3142.54   511.4 3148.28   514.3 3148.67   563.7 3148.72
#Mann= 6 ,-1,0
       0     .03       0     100     .08       0  417.03      .1       0
  437.03     .08       0  472.79    .045       0   493.8     .08       0
#XS Ineff= 2 , 0
          214.65 3146.99
Permanent Ineff=
       F       F
Bank Sta=472.79,493.8
XS Rating Curve= 0 ,0
Exp/Cntr(USF)=0,0
Exp/Cntr=0.3,0.1

Type RM Length L Ch R = 1 ,18569   ,177.2,175.3,177
XS GIS Cut Line= 3
2206549.26695278471647.8064915142206620.66611834471710.418067469
 2206800.8117053472019.082152439
#Sta/Elev= 30
       0 3153.47    14.2 3153.11    25.1 3151.44    35.8 3151.27    51.2 3149.77
   101.9 3147.79   109.9 3146.76   121.3 3146.75   125.9 3145.87   134.6 3142.88
   137.6 3142.35   144.5 3142.08   165.4 3142.45   167.6  3142.3   175.6  3140.5
   186.2 3139.52   190.8 3139.65   195.4 3140.42   204.7 3142.06   213.9 3142.57
   241.7 3141.91   274.2 3143.07   283.4 3142.78   301.9 3143.81   321.8 3143.72
     339 3144.77   357.5 3144.17   403.5 3144.74   431.6 3147.46   452.4 3148.49
#Mann= 6 ,-1,0
       0     .03       0      30      .1       0  164.96     .08       0
   175.6    .045       0   195.4     .08       0  394.96     .03       0
Bank Sta=175.6,195.4
XS Rating Curve= 0 ,0
Exp/Cntr(USF)=0,0
Exp/Cntr=0.3,0.1

Type RM Length L Ch R = 1 ,18394   ,214.7,216.2,215.5
XS GIS Cut Line= 5
2206500.67383714471765.9355378382206537.64326525471833.658646308
2206601.22483284471951.5508944832206619.99235459472010.269593118
2206689.61880257472051.603458383
#Sta/Elev= 30
       0  3150.7     8.3 3149.51    25.6 3145.77    35.6 3144.68    40.2 3144.61
    53.8 3145.12    67.5  3144.8    81.2 3144.09    90.2 3142.77   111.1 3141.55
   131.1 3141.52   140.7 3141.86   153.9 3141.01     163 3141.42   175.2 3141.31
   176.6 3141.21     185 3139.28   190.2 3138.74   202.7 3139.28   208.4 3140.11
   212.8 3142.49     217 3143.23   233.9 3142.69   249.7  3143.9   263.2 3144.47
   292.5 3144.25   298.4 3144.75     310 3146.61   317.6 3147.41   353.7 3147.99
#Mann= 4 ,-1,0
       0      .1       0  117.16     .03       0     185    .045       0
   202.7     .03       0
Bank Sta=185,202.7
XS Rating Curve= 0 ,0
Exp/Cntr(USF)=0,0
Exp/Cntr=0.3,0.1

Type RM Length L Ch R = 1 ,18177   ,78.7,74.6,71.9
XS GIS Cut Line= 2
2206346.02166501471835.3962632032206523.03385737472263.476769196
#Sta/Elev= 30
       0 3148.61    19.2 3147.99    30.6 3148.38    42.8 3147.28    55.1  3145.6
    84.2 3144.41   132.2  3143.4   149.1 3143.82   168.4 3143.78     201 3141.76
   235.7 3141.56   248.7 3139.52     253 3138.73   256.9 3138.55   261.6 3139.51
   267.3 3140.85   283.3 3142.49   291.9 3145.17     297 3145.82   303.1 3145.84
   330.9 3144.18   348.2 3144.03   361.3 3144.41   369.9 3145.45   387.2 3148.64
   400.1 3149.94   413.4 3150.76   426.1 3152.17   434.8 3152.59   463.2 3156.77
#Mann= 5 ,-1,0
       0     .05       0      10     .03       0   248.7    .045       0
   261.6     .03       0     360     .08       0
#XS Ineff= 2 , 0
                          300.56         3147.12
Permanent Ineff=
       F       F
Bank Sta=248.7,261.6
XS Rating Curve= 0 ,0
Exp/Cntr(USF)=0,0
Exp/Cntr=0.3,0.1

Type RM Length L Ch R = 1 ,18103   ,227.1,208.2,179.6
XS GIS Cut Line= 3
2206267.49934618471913.2916433352206424.89554995472181.869846361
 2206493.2885013472249.205857968
#Sta/Elev= 30
       0 3145.18     6.3 3145.38    17.2 3144.93    27.7 3145.72    35.5 3145.25
    44.3 3144.14    70.6 3142.91   117.3 3141.97   143.6 3141.06   157.5 3141.24
   166.8 3140.51   180.7 3141.31   187.5 3140.42   193.3 3139.12   203.9 3138.48
   213.8 3139.17   222.9 3141.13   237.2 3141.66   260.6 3143.98   268.8  3144.5
   278.2 3144.59   296.6 3144.12   305.9 3144.62   321.7 3144.22   338.8 3144.67
     344 3145.26   349.9 3146.43   366.4 3148.79   394.5 3151.95   407.3 3153.06
#Mann= 5 ,-1,0
       0     .05       0     160     .03       0   193.3    .045       0
   213.8     .03       0   341.3     .08       0
#XS Ineff= 2 , 0
                          277.46          3145.8
Permanent Ineff=
       F       F
Bank Sta=193.3,213.8
XS Rating Curve= 0 ,0
Exp/Cntr(USF)=0,0
Exp/Cntr=0.3,0.1

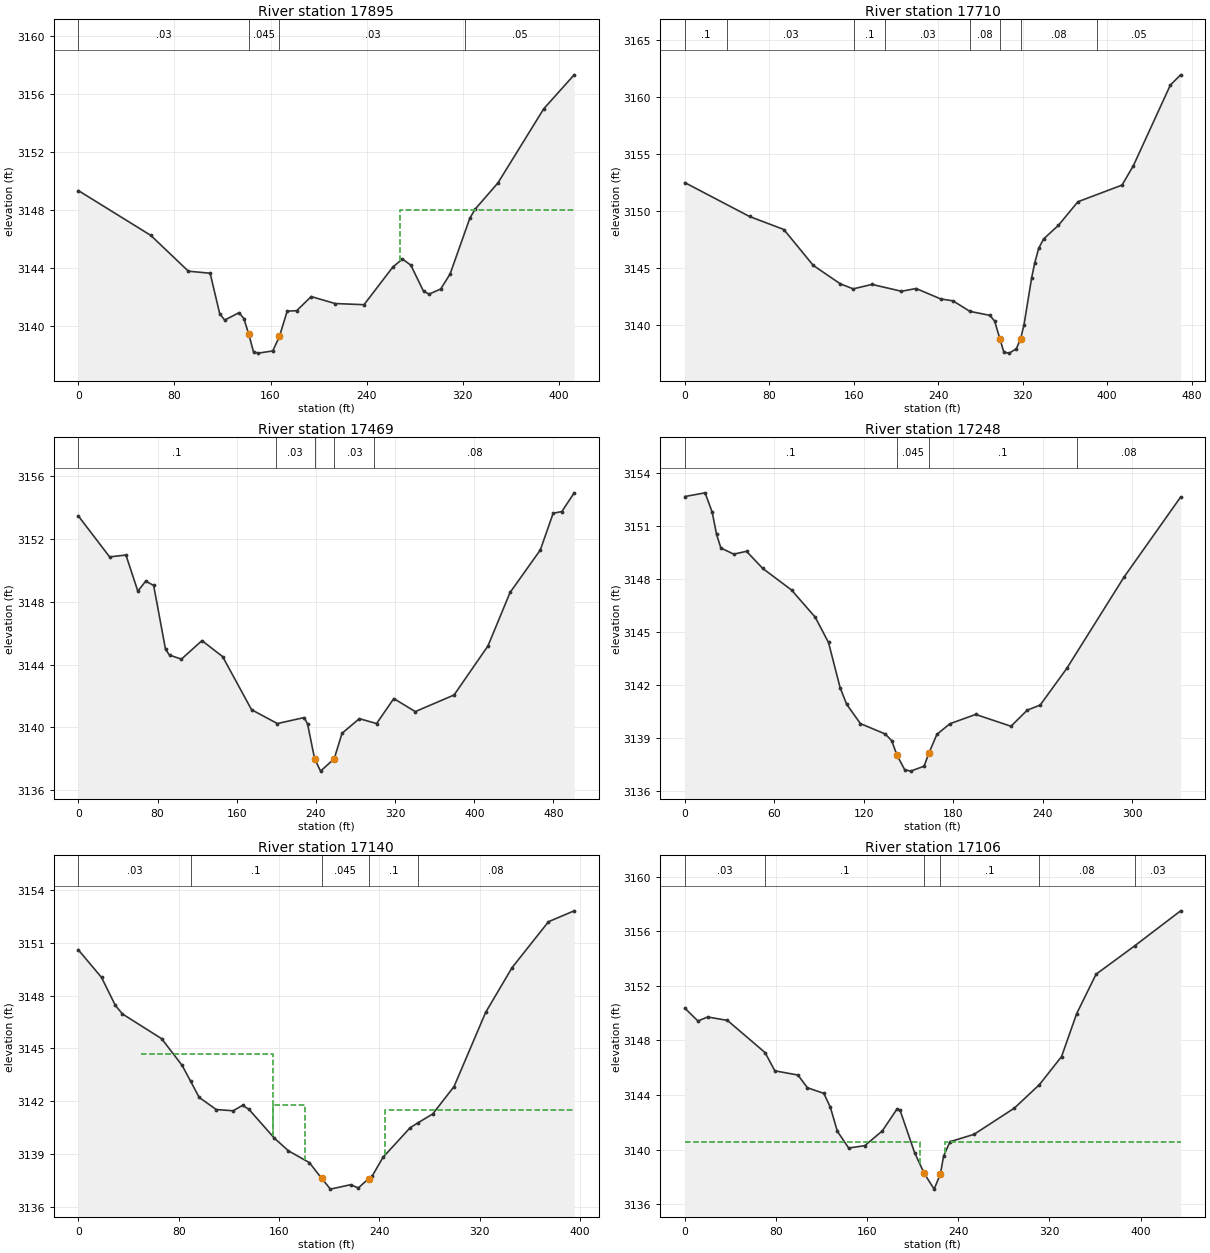
Type RM Length L Ch R = 1 ,17895   ,161.5,184.2,204.1
XS GIS Cut Line= 4
2206117.98280154472159.6993676772206195.12412908472224.417773456
2206366.40234504472220.3909159932206442.92802269472338.405439294
#Sta/Elev= 30
       0 3149.37    60.3 3146.28    91.6 3143.81   109.7 3143.67   117.7 3140.87
   121.8 3140.44   133.8 3140.95   137.8 3140.54   141.8 3139.48   145.8 3138.25
   149.8 3138.16   161.8 3138.31   167.4 3139.31   173.8 3141.05   181.8 3141.09
   193.8 3142.06   213.8 3141.58   237.8  3141.5   261.8  3144.1   269.8 3144.65
   276.8 3144.22   287.3 3142.43     292 3142.23   301.6 3142.58   309.4 3143.61
   325.9 3147.47   330.2 3148.08   349.2 3149.89   387.4 3155.01   412.7 3157.35
#Mann= 4 ,-1,0
       0     .03       0   141.8    .045       0   167.4     .03       0
  322.02     .05       0
#XS Ineff= 2 , 0
                          268.05         3148.05
Permanent Ineff=
       F       F
Bank Sta=141.8,167.4
XS Rating Curve= 0 ,0
Exp/Cntr(USF)=0,0
Exp/Cntr=0.3,0.1

Type RM Length L Ch R = 1 ,17710   ,239.4,241.7,244.6
XS GIS Cut Line= 2
2206055.21592044 472124.395760922206293.64050605472528.995057724
#Sta/Elev= 30
       0  3152.5    61.3 3149.53    93.8 3148.39   121.6 3145.25   147.3 3143.63
   159.5 3143.19   177.3 3143.58   205.2 3142.98   219.1 3143.22   242.3 3142.31
     254 3142.14     270 3141.22   288.8 3140.87   293.4 3140.38   298.43138.822
   302.2 3137.64   307.3 3137.56   313.9 3137.93  318.03 3138.81   321.3 3140.06
   328.5 3144.16   331.4 3145.45   335.2 3146.75   339.8 3147.56   353.8 3148.75
   372.3 3150.82   414.1 3152.28   424.9 3153.99   459.9 3161.05   469.6 3161.94
#Mann= 8 ,-1,0
       0      .1       0      40     .03       0     160      .1       0
     190     .03       0     270     .08       0   298.4    .045       0
  318.03     .08       0     390     .05       0
Bank Sta=298.4,318.03
XS Rating Curve= 0 ,0
Exp/Cntr(USF)=0,0
Exp/Cntr=0.3,0.1

Type RM Length L Ch R = 1 ,17469   ,218.5,220.9,219.1
XS GIS Cut Line= 3
2205937.80987449 472173.164426162205932.39113391472312.245434436
2206075.08463591472644.594856811
#Sta/Elev= 30
       0 3153.47    31.6 3150.86    48.1 3150.98    60.1 3148.68    68.1 3149.32
    76.1 3149.04    88.1 3144.97    92.1 3144.61   104.1 3144.35   124.9 3145.53
   145.8 3144.51     175 3141.13   201.1 3140.25   228.1 3140.63   231.6 3140.22
  238.65 3138.02   244.7 3137.22   258.5 3138.01   266.4 3139.63   283.9 3140.56
   301.3 3140.25   318.7 3141.84   340.4 3141.01   379.6 3142.07   413.8 3145.19
   436.2  3148.6   466.7  3151.3   479.7 3153.64   488.5 3153.75   500.9 3154.94
#Mann= 5 ,-1,0
       0      .1       0  199.19     .03       0  238.65    .045       0
   258.5     .03       0  299.19     .08       0
Bank Sta=238.65,258.5
XS Rating Curve= 0 ,0
Exp/Cntr(USF)=0,0
Exp/Cntr=0.3,0.1

Type RM Length L Ch R = 1 ,17248   ,115.8,107.4,101.1
BEGIN DESCRIPTION:
xs 4
END DESCRIPTION:
XS GIS Cut Line= 3
2205725.79152154472325.9736723882205778.01878815472402.697497997
2205869.87473067472624.245095525
#Sta/Elev= 30
       0 3152.64    13.6 3152.85    18.4 3151.75    21.3  3150.5    24.2 3149.73
    32.8 3149.38    41.4 3149.54    52.3 3148.57    71.6 3147.35    87.5 3145.81
    96.4 3144.38   104.2 3141.82   108.6 3140.88   117.8 3139.79   134.5  3139.2
   138.8 3138.82   142.3 3138.01   147.5 3137.18   151.5  3137.1   160.5 3137.38
   163.7 3138.11   169.1 3139.18   177.8 3139.78   195.1 3140.31   218.8 3139.64
   229.7 3140.55   238.4 3140.84   256.2 3142.91   294.7 3148.09   332.6 3152.61
#Mann= 4 ,-1,0
       0      .1       0   142.3    .045       0   163.7      .1       0
  262.81     .08       0
Bank Sta=142.3,163.7
XS Rating Curve= 0 ,0
Exp/Cntr(USF)=0,0
Exp/Cntr=0.5,0.3

Type RM Length L Ch R = 1 ,17140   ,37.1,34.8,36.4
BEGIN DESCRIPTION:
xs 3
END DESCRIPTION:
XS GIS Cut Line= 6
2205560.37629042472391.3069691752205612.04171529472449.930279796
2205681.00213069472484.3403027162205739.93273902 472544.84645738
2205794.65495251 472608.535236622205863.95956682472627.500590035
#Sta/Elev= 30
       0 3150.61    18.5 3149.04    29.5 3147.45    35.2 3146.96    66.5 3145.55
    82.8 3144.03    89.5 3143.14    96.4 3142.21     110 3141.52   123.5 3141.45
     131 3141.76   136.1 3141.53   156.4 3139.89   167.6 3139.17   184.3  3138.5
     194 3137.61   201.1 3136.99   217.1 3137.24   223.4 3137.06   231.6 3137.59
   234.6 3137.76     243  3138.8   264.6 3140.48   270.8 3140.76   282.7 3141.27
   299.7 3142.83   324.9 3147.05     346  3149.6     375 3152.21   395.5 3152.83
#Mann= 5 ,-1,0
       0     .03       0    89.5      .1       0     194    .045       0
   231.6      .1       0   270.8     .08       0
#XS Ineff= 3 ,-1
      50     155  3144.7     155     181  3141.8   244.6   424.6  3141.5
Permanent Ineff=
       F       F       F
Bank Sta=194,231.6
XS Rating Curve= 0 ,0
Exp/Cntr(USF)=0,0
Exp/Cntr=0.5,0.3

Type RM Length L Ch R = 1 ,17106   ,67.9,70.9,73
BEGIN DESCRIPTION:
xs 2
END DESCRIPTION:
XS GIS Cut Line= 6
2205543.50054035472398.5554195392205558.24196844472434.810089504
2205586.72418736472460.8308820992205648.61147785472505.839820641
2205788.24214625472634.2099540262205873.78799886472665.916792871
#Sta/Elev= 30
       0 3150.37    11.5 3149.43    20.1 3149.72    37.4 3149.47    70.5 3147.11
      79 3145.78    99.3 3145.47   107.6 3144.54     122 3144.13   127.7 3143.12
   133.9 3141.35   143.8 3140.13   157.9  3140.3   173.3 3141.38   186.2 3142.98
   188.8 3142.92   201.6  3139.8   210.1 3138.27   218.8 3137.12   224.3 3138.23
   227.1 3139.54   232.7 3140.59   253.8 3141.13   289.2 3143.05   311.2 3144.77
   330.6 3146.82   343.9 3149.97   360.9 3152.85     395 3154.94   435.1 3157.49
#Mann= 6 ,-1,0
       0     .03       0    70.5      .1       0   210.1    .045       0
   224.3      .1       0   311.2     .08       0     395     .03       0
#XS Ineff= 2 , 0
           206.1 3140.58   228.3         3140.58
Permanent Ineff=
       F       F
Bank Sta=210.1,224.3
XS Rating Curve= 0 ,0
Exp/Cntr(USF)=0,0
Exp/Cntr=0.5,0.3