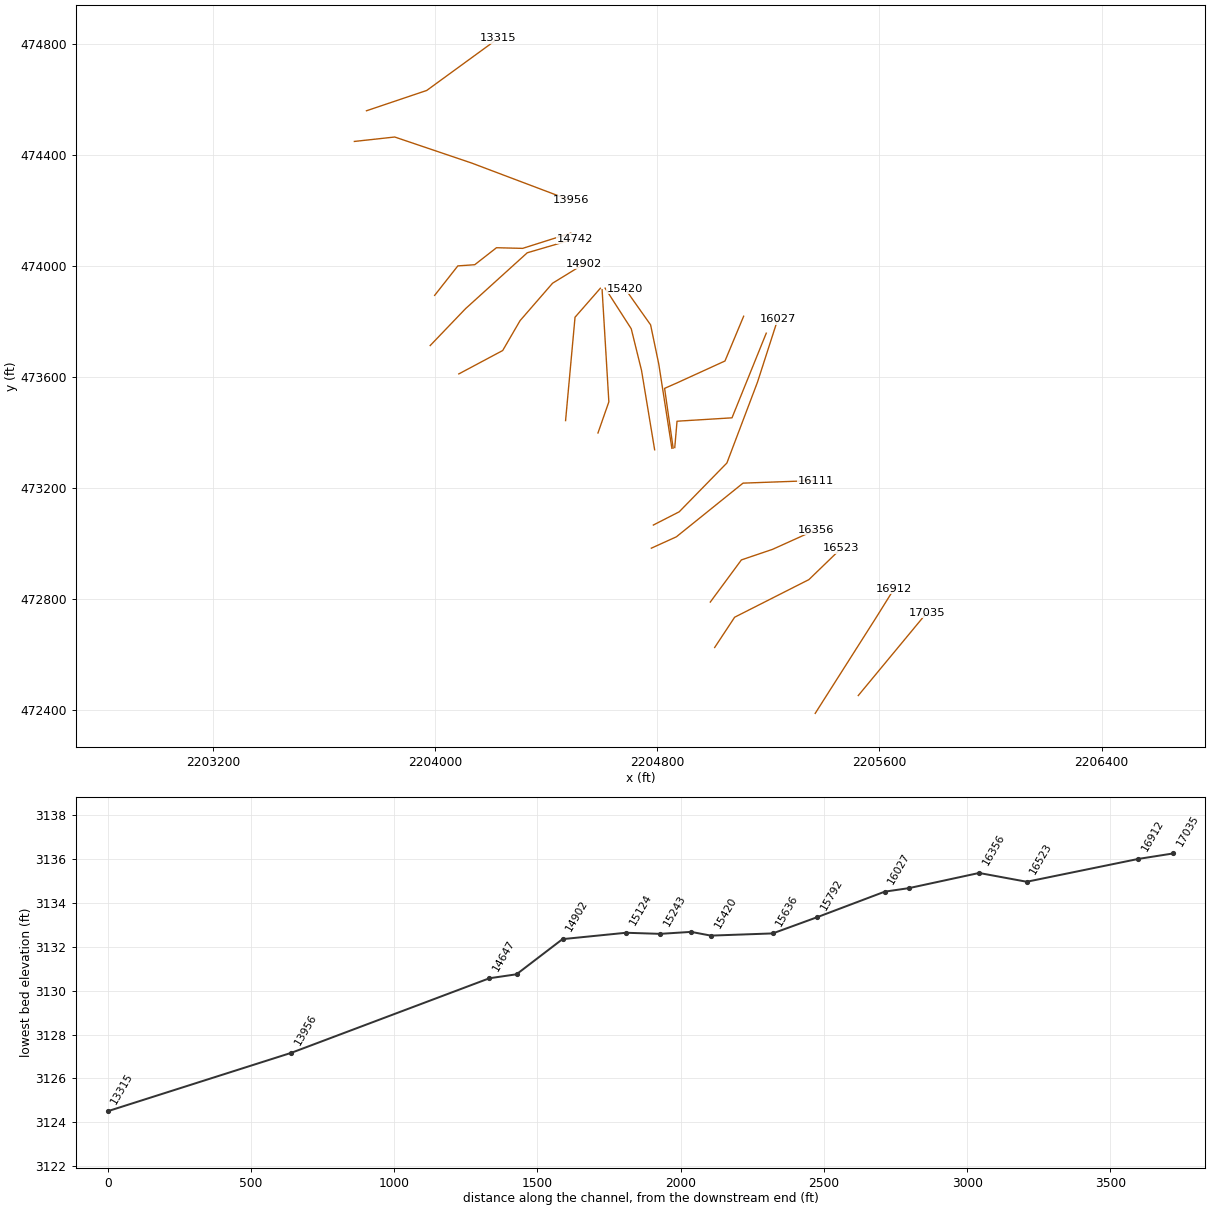
HEC-RAS study BIGLAURLCK.prj: BIGLAURLCK

--- BIGLAURLCK.g01 (geometry) --- (continued)

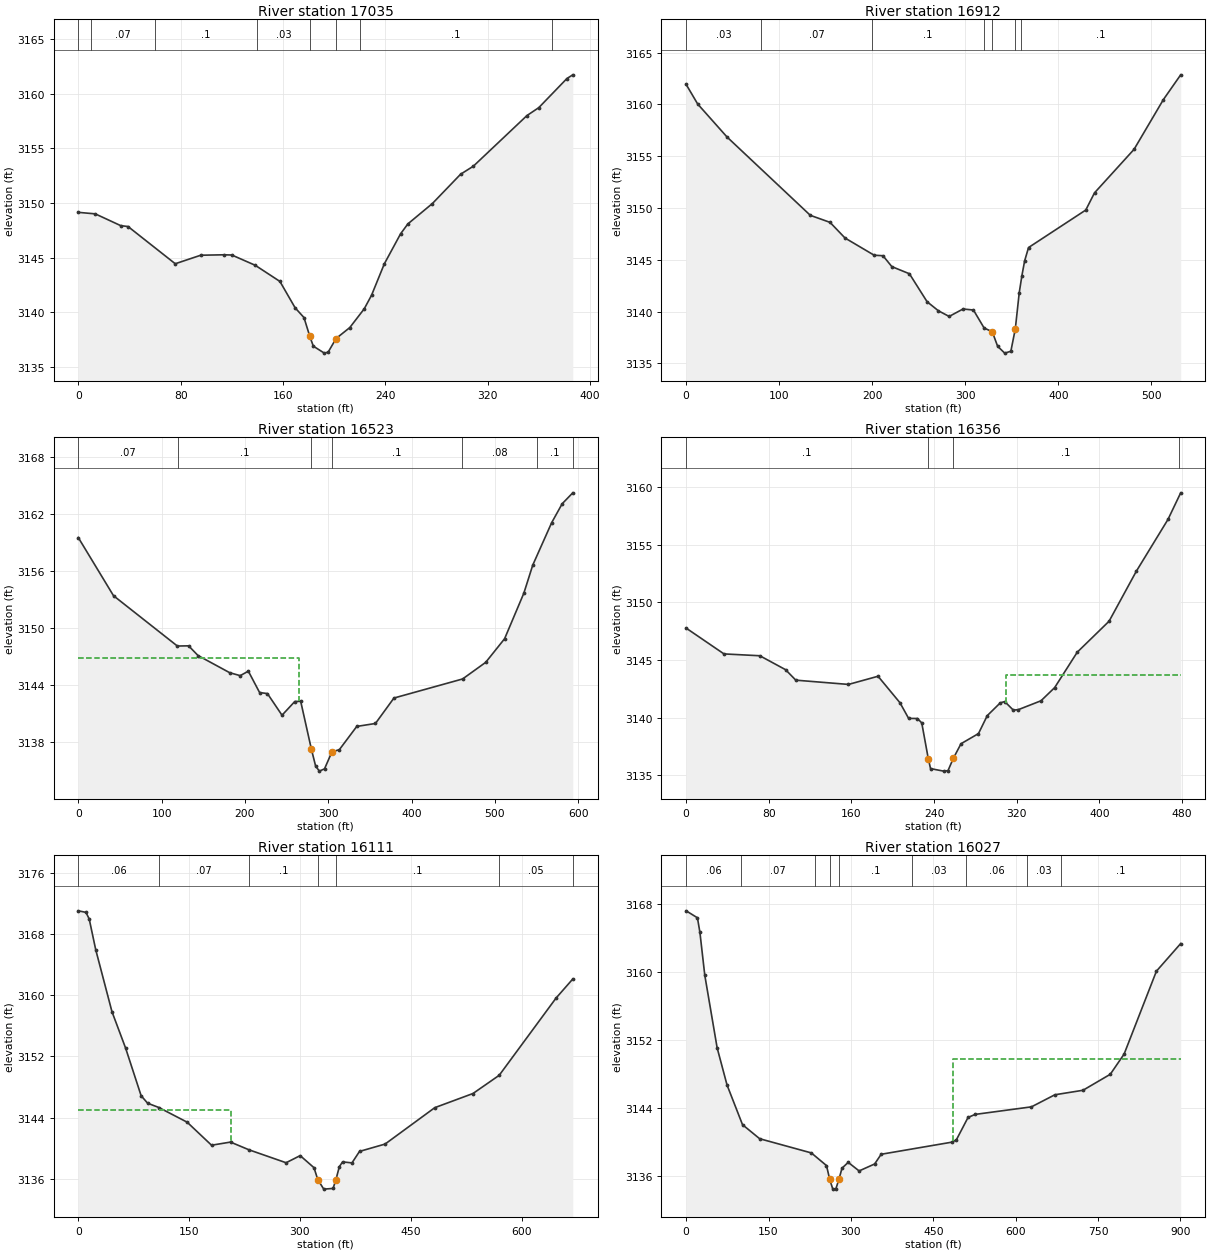
Type RM Length L Ch R = 1 ,17035   ,119.1,122.2,124.7
XS GIS Cut Line= 2
2205523.69656517472450.9534480362205770.11059091472748.777594261
#Sta/Elev= 30
       0 3149.14    13.3    3149    33.2 3147.92    38.9 3147.84    75.8 3144.43
    95.7 3145.21   113.7 3145.25     120 3145.23   138.3 3144.29   157.6 3142.81
   169.5 3140.39   176.4  3139.5   180.9  3137.8   183.7 3136.88   192.3 3136.24
   195.3 3136.33   201.5 3137.58   212.2 3138.58   223.5  3140.3   229.2 3141.54
   239.2 3144.42   251.9 3147.17   257.6 3148.08   276.8 3149.95   298.8 3152.63
   308.8 3153.37   350.7 3158.01   359.9 3158.73   381.9  3161.4   386.5 3161.74
#Mann= 8 ,-1,0
       0     .03       0      10     .07       0      60      .1       0
     140     .03       0   180.9    .045       0   201.5     .03       0
     220      .1       0     370     .03       0
Bank Sta=180.9,201.5
XS Rating Curve= 0 ,0
Exp/Cntr(USF)=0,0
Exp/Cntr=0.3,0.1

Type RM Length L Ch R = 1 ,16912   ,399.5,389.8,375.6
XS GIS Cut Line= 3
2205368.63908672472386.6752531322205590.84932813472736.438313275
2205652.77647515472835.709779581
#Sta/Elev= 30
       0 3161.92    12.4 3160.03    43.9 3156.85   133.4 3149.29   154.6 3148.61
   170.7  3147.1     202 3145.44   211.5 3145.39     221 3144.34   239.9 3143.65
   258.9 3140.95     271 3140.08   282.6 3139.53   297.5 3140.25   308.7 3140.15
   320.2 3138.41   328.9 3138.06   334.7 3136.65   342.3 3135.99   348.9 3136.17
   353.7 3138.34   357.9 3141.82   360.8 3143.48   363.7 3144.89   367.9 3146.18
   429.4  3149.8   438.8 3151.46   481.3 3155.66   512.8 3160.46   531.4 3162.85
#Mann= 7 ,-1,0
       0     .03       0      80     .07       0     200      .1       0
     320     .03       0   328.9    .045       0   353.7     .03       0
     360      .1       0
Bank Sta=328.9,353.7
XS Rating Curve= 0 ,0
Exp/Cntr(USF)=0,0
Exp/Cntr=0.3,0.1

Type RM Length L Ch R = 1 ,16523   ,169.4,166.4,163.1
XS GIS Cut Line= 4
2205006.70536243472624.1049876382205078.63839884472733.151496123
 2205346.0329063472868.6741084612205463.14888451472982.054837975
#Sta/Elev= 30
       0 3159.56    42.3 3153.43   118.9 3148.13   132.4 3148.15   143.7 3147.13
   181.7 3145.32   194.3 3145.01   204.1 3145.48   217.6 3143.23     227 3143.12
   244.5 3140.84   259.8 3142.28   266.9 3142.31   279.6 3137.32   284.8 3135.49
   289.3 3134.95   295.5 3135.19   304.4 3136.98   313.3 3137.21   334.2 3139.66
   356.6 3139.97   378.8 3142.65   461.2 3144.66   488.9 3146.41   511.6  3148.9
   534.7  3153.7   545.4 3156.66   568.1 3161.13   580.7 3163.12   593.4 3164.27
#Mann= 7 ,-1,0
       0     .07       0     120      .1       0   279.6    .045       0
   304.4      .1       0  460.41     .08       0  550.41      .1       0
  593.42     .08       0
#XS Ineff= 2 , 0
          264.52 3146.86
Permanent Ineff=
       F       F
Bank Sta=279.6,304.4
XS Rating Curve= 0 ,0
Exp/Cntr(USF)=0,0
Exp/Cntr=0.3,0.1

Type RM Length L Ch R = 1 ,16356   ,236.4,244.9,251.9
XS GIS Cut Line= 4
2204990.94110286472787.763958714 2205102.9326875472939.607763343
2205215.06934204472977.6737872862205371.33608483473048.291711637
#Sta/Elev= 30
       0 3147.77    36.6 3145.53    71.3 3145.37    96.2 3144.16   106.1 3143.25
   157.1 3142.88   185.7 3143.59   206.9 3141.29   215.3 3139.93   223.8 3139.92
     228 3139.54   234.3 3136.44   236.5 3135.57   249.1 3135.35   253.4 3135.39
   258.5 3136.45     266 3137.73   282.9 3138.61   291.4 3140.17     304 3141.28
   308.3 3141.39   316.6 3140.65   321.5 3140.69   343.4 3141.46   356.6  3142.6
   378.5 3145.68   409.3 3148.37   435.6  3152.7   466.3 3157.21   478.6 3159.52
#Mann= 4 ,-1,0
       0      .1       0   234.3    .045       0   258.5      .1       0
   477.1     .05       0
#XS Ineff= 2 , 0
                          309.58          3143.7
Permanent Ineff=
       F       F
Bank Sta=234.3,258.5
XS Rating Curve= 0 ,0
Exp/Cntr(USF)=0,0
Exp/Cntr=0.3,0.1

Type RM Length L Ch R = 1 ,16111   ,81.6,84.4,86.8
XS GIS Cut Line= 4
2204778.69493764472981.8522570432204868.67826374473022.701091233
2205108.79835076 473216.214387232205370.86421107473225.686912523
#Sta/Elev= 30
       0 3171.04    10.4 3170.84    14.8 3169.98    23.6 3165.97    45.6 3157.86
    64.1 3153.09    85.1 3146.87    93.9 3145.89   109.1 3145.33   147.4 3143.41
   180.4  3140.4   206.1 3140.81   231.1  3139.8   281.3 3138.11   300.4 3139.04
   319.1 3137.46   324.2 3135.91   332.3 3134.66   344.9 3134.75  348.78  3135.9
   353.4  3137.6   357.8 3138.22   370.5 3138.09   380.7 3139.59   415.3 3140.55
   482.6 3145.31   534.3 3147.16   569.8 3149.54   646.7 3159.63   669.4 3162.13
#Mann= 7 ,-1,0
       0     .06       0   109.1     .07       0   231.1      .1       0
   324.2    .045       0  348.78      .1       0   569.8     .05       0
   669.4      .1       0
#XS Ineff= 2 , 0
           206.1    3145
Permanent Ineff=
       F       F
Bank Sta=324.2,348.78
XS Rating Curve= 0 ,0
Exp/Cntr(USF)=0,0
Exp/Cntr=0.3,0.1

Type RM Length L Ch R = 1 ,16027   ,248.5,235.4,220.8
XS GIS Cut Line= 5
2204785.95702982473065.2679386462204878.97825174473112.871577829
2205050.71038197473288.8243482092205160.86261461473580.122575175
2205234.07748018473807.229856236
#Sta/Elev= 30
       0 3167.24    20.5 3166.42      25 3164.72    33.9 3159.66    56.4 3151.12
    74.4 3146.75   102.6 3142.08   133.8 3140.43   227.9 3138.76   255.5 3137.27
   261.4 3135.64     267  3134.5   272.6 3134.55   278.2 3135.65   283.7 3136.96
     295 3137.65   314.9 3136.64   343.2 3137.46     355  3138.6   483.3 3140.02
   491.9 3140.29   513.2 3142.93   526.1 3143.29   628.7 3144.18   671.3  3145.6
   722.5 3146.13   772.2 3148.01   797.4 3150.39   856.2 3160.14   900.4 3163.39
#Mann= 9 ,-1,0
       0     .06       0     100     .07       0  234.49      .1       0
   261.4    .045       0   278.2      .1       0  410.36     .03       0
  510.36     .06       0  620.36     .03       0  681.79      .1       0
#XS Ineff= 2 , 0
                          486.01         3149.83
Permanent Ineff=
       F       F
Bank Sta=261.4,278.2
XS Rating Curve= 0 ,0
Exp/Cntr(USF)=0,0
Exp/Cntr=0.3,0.1

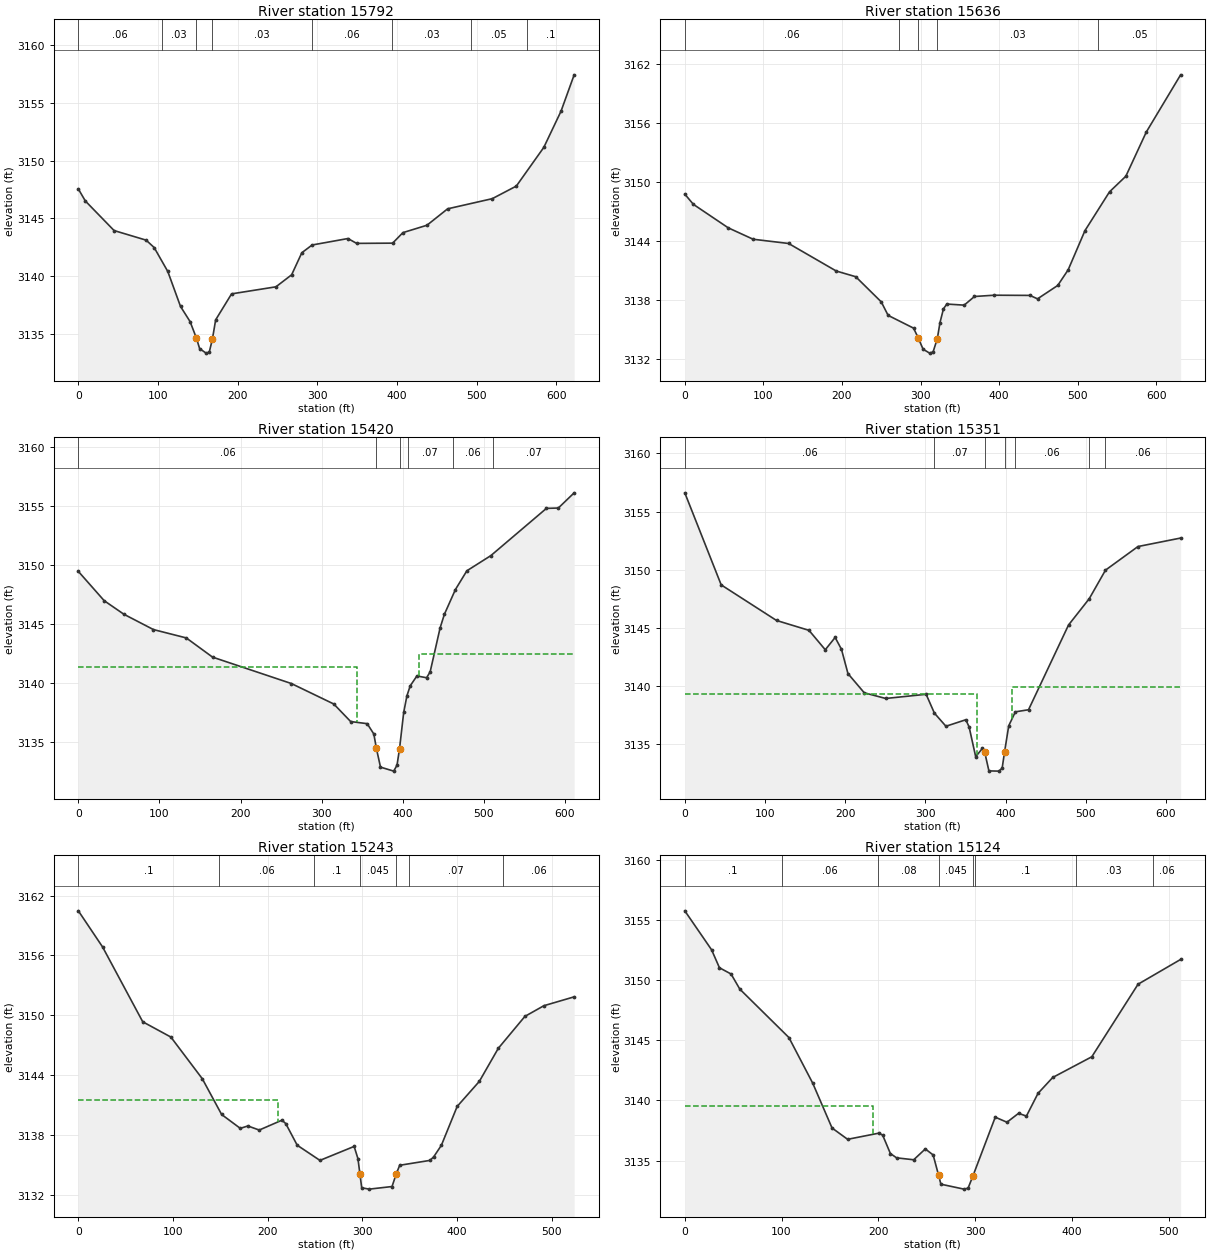
Type RM Length L Ch R = 1 ,15792   ,147.9,155.6,163.8
XS GIS Cut Line= 4
2204863.03398775473344.4190798362204871.16677092473439.301550212
2205069.06449485473451.5007249752205192.41170634 473756.48009404
#Sta/Elev= 30
       0 3147.55     8.8 3146.51    44.9 3143.95    85.1 3143.12    95.2 3142.48
   112.3 3140.41   128.3 3137.38   140.3 3136.07   148.3 3134.63   152.3 3133.73
   160.4 3133.34   164.4 3133.43   168.4 3134.58   172.4 3136.22   192.4 3138.47
   248.1 3139.08   267.8 3140.12   280.6 3142.03   293.5  3142.7   338.5 3143.26
   349.4 3142.84   394.6 3142.86   407.5 3143.77   437.7 3144.41   463.6 3145.83
   519.7 3146.71   549.9  3147.8   584.4 3151.15     606 3154.28   622.5 3157.43
#Mann= 8 ,-1,0
       0     .06       0  105.23     .03       0   148.3    .045       0
   168.4     .03       0   293.5     .06       0   393.5     .03       0
   493.5     .05       0   563.5      .1       0
Bank Sta=148.3,168.4
XS Rating Curve= 0 ,0
Exp/Cntr(USF)=0,0
Exp/Cntr=0.3,0.1

Type RM Length L Ch R = 1 ,15636   ,179,216,244.2
BEGIN DESCRIPTION:
xs 4
END DESCRIPTION:
XS GIS Cut Line= 5
2204857.17370972473342.3903517182204826.40505195473557.693951019
2204867.44898875473575.6867381492205043.78532409473656.241587422
2205110.98480946473817.497038524
#Sta/Elev= 30
       0 3148.77    10.9 3147.73    55.3 3145.34      87 3144.18   132.1 3143.75
   192.7 3140.95   217.5 3140.37     250 3137.81   258.7 3136.44   291.1 3135.14
  296.88 3134.17   303.2    3133   311.5  3132.6   315.9 3132.72   321.3 3134.07
   324.7  3135.7   329.1  3137.1   333.4 3137.59   355.5 3137.48   368.6 3138.36
   393.8 3138.49   439.2 3138.47   448.8 3138.12   474.5 3139.48   487.8 3141.07
   509.2 3145.06   540.4    3149   561.2 3150.59   587.2 3155.08   630.9  3160.9
#Mann= 5 ,-1,0
       0     .06       0  272.31     .03       0  296.88    .045       0
   321.3     .03       0  526.17     .05       0
Bank Sta=296.88,321.3
XS Rating Curve= 0 ,0
Exp/Cntr(USF)=0,0
Exp/Cntr=0.5,0.3

Type RM Length L Ch R = 1 ,15420   ,69.6,69,70.5
BEGIN DESCRIPTION:
xs 3
END DESCRIPTION:
XS GIS Cut Line= 4
2204852.65955471473341.6573352762204805.54704415473644.584054992
 2204775.9987991473786.4156312342204683.79223697473917.104131035
#Sta/Elev= 30
       0 3149.46    31.9 3146.97    56.2 3145.82    92.6 3144.52   133.1 3143.81
   165.5 3142.18   262.6 3139.94     315  3138.2   335.8 3136.71   356.2 3136.53
   364.4 3135.65  367.53 3134.43   372.6 3132.84   388.9  3132.5     393 3133.01
   396.1 3134.42   401.2 3137.48   405.2  3138.9   409.3 3139.75   417.5 3140.58
   429.4 3140.43   433.8 3140.92   446.1 3144.66   451.4 3145.82     465 3147.92
   479.1 3149.51   508.7  3150.8   577.2 3154.81   591.9 3154.84   611.4 3156.13
#Mann= 6 ,-1,0
       0     .06       0  367.53    .045       0   396.1     .06       0
  406.57     .07       0  461.45     .06       0  511.45     .07       0
#XS Ineff= 2 , 0
           343.5 3141.36   420.1         3142.41
Permanent Ineff=
       F       F
Bank Sta=367.53,396.1
XS Rating Curve= 0 ,0
Exp/Cntr(USF)=0,0
Exp/Cntr=0.5,0.3

Type RM Length L Ch R = 1 ,15351   ,111.7,107.9,103.1
BEGIN DESCRIPTION:
xs 2
c/e 0.5/0.7 used to correct drawdown between xs 15347 and xs 15239
END DESCRIPTION:
XS GIS Cut Line= 4
2204790.57884924473336.3499060832204743.37711689473622.231830571
2204706.34185846473772.2897973822204612.30840255473918.740277132
#Sta/Elev= 30
       0 3156.61    45.4 3148.69   114.4 3145.63   154.9 3144.78   175.2 3143.11
   187.5 3144.17   195.4 3143.15   203.5 3141.06   223.8 3139.41   250.6 3138.92
     301 3139.28   311.3 3137.66   325.7 3136.53   350.5 3137.09   354.6 3136.47
   362.8 3133.91   371.1 3134.62   374.1 3134.28   379.3 3132.69   391.7 3132.67
   395.8 3132.92   398.8 3134.31     404 3136.57   412.3 3137.77   428.7 3137.95
   478.6 3145.24   504.4  3147.5   524.7 3149.96   565.2 3151.99   618.4 3152.72
#Mann= 7 ,-1,0
       0     .06       0   311.3     .07       0   374.1    .045       0
   398.8     .07       0   412.3     .06       0   504.4     .07       0
   524.7     .06       0
#XS Ineff= 2 , 0
           364.8 3139.32   408.2         3139.88
Permanent Ineff=
       F       F
Bank Sta=374.1,398.8
XS Rating Curve= 0 ,0
Exp/Cntr(USF)=0,0
Exp/Cntr=0.7,0.5

Type RM Length L Ch R = 1 ,15243   ,123.8,119,114.8
XS GIS Cut Line= 3
2204586.56044007473396.9659476792204625.73901077473509.097719007
2204601.42127723473913.042292828
#Sta/Elev= 30
       0 3160.47    25.6 3156.85      68 3149.35    97.7 3147.82   130.9 3143.64
   151.3 3140.06     171 3138.67     179 3138.91     191  3138.5     215 3139.49
     219 3139.15   231.1 3136.98   255.1 3135.46   291.2 3136.86   295.2 3135.64
  297.26 3134.14   299.2 3132.71   307.2 3132.58   331.2 3132.84   335.8 3134.14
   339.3 3134.97   371.3 3135.46   375.3 3135.83   383.3 3136.97     400 3140.87
   423.4 3143.38   443.4 3146.69   471.5 3149.89   491.5 3150.96   523.5 3151.85
#Mann= 7 ,-1,0
       0      .1       0  148.78     .06       0  248.78      .1       0
  297.26    .045       0   335.8      .1       0  348.78     .07       0
  448.78     .06       0
#XS Ineff= 2 , 0
          211.27 3141.52
Permanent Ineff=
       F       F
Bank Sta=297.26,335.8
XS Rating Curve= 0 ,0
Exp/Cntr(USF)=0,0
Exp/Cntr=0.3,0.1

Type RM Length L Ch R = 1 ,15124   ,234.9,221.8,198.1
XS GIS Cut Line= 3
2204469.90356185473441.5732201832204503.95547158473813.947329809
2204595.12671376  473918.2999564
#Sta/Elev= 30
       0 3155.76    27.7 3152.52    35.8 3151.03    47.8 3150.51    56.9 3149.25
   107.6 3145.23   132.2 3141.44   152.2 3137.71   168.3 3136.77   200.5 3137.28
   204.5 3137.12   212.5 3135.59   218.9 3135.23   236.6 3135.07   248.6 3135.97
   256.7 3135.47   262.3 3133.79   264.7 3133.04   288.5 3132.63   292.8 3132.71
   297.7  3133.7   320.9 3138.61     333 3138.19     345 3138.93   353.1  3138.7
   365.1 3140.59   380.3 3141.91   420.7 3143.63   468.5 3149.66   512.5 3151.72
#Mann= 8 ,-1,0
       0      .1       0     100     .06       0     200     .08       0
   262.3    .045       0   297.7     .08       0     300      .1       0
  403.93     .03       0  483.93     .06       0
#XS Ineff= 2 , 0
          194.03 3139.57
Permanent Ineff=
       F       F
Bank Sta=262.3,297.7
XS Rating Curve= 0 ,0
Exp/Cntr(USF)=0,0
Exp/Cntr=0.3,0.1

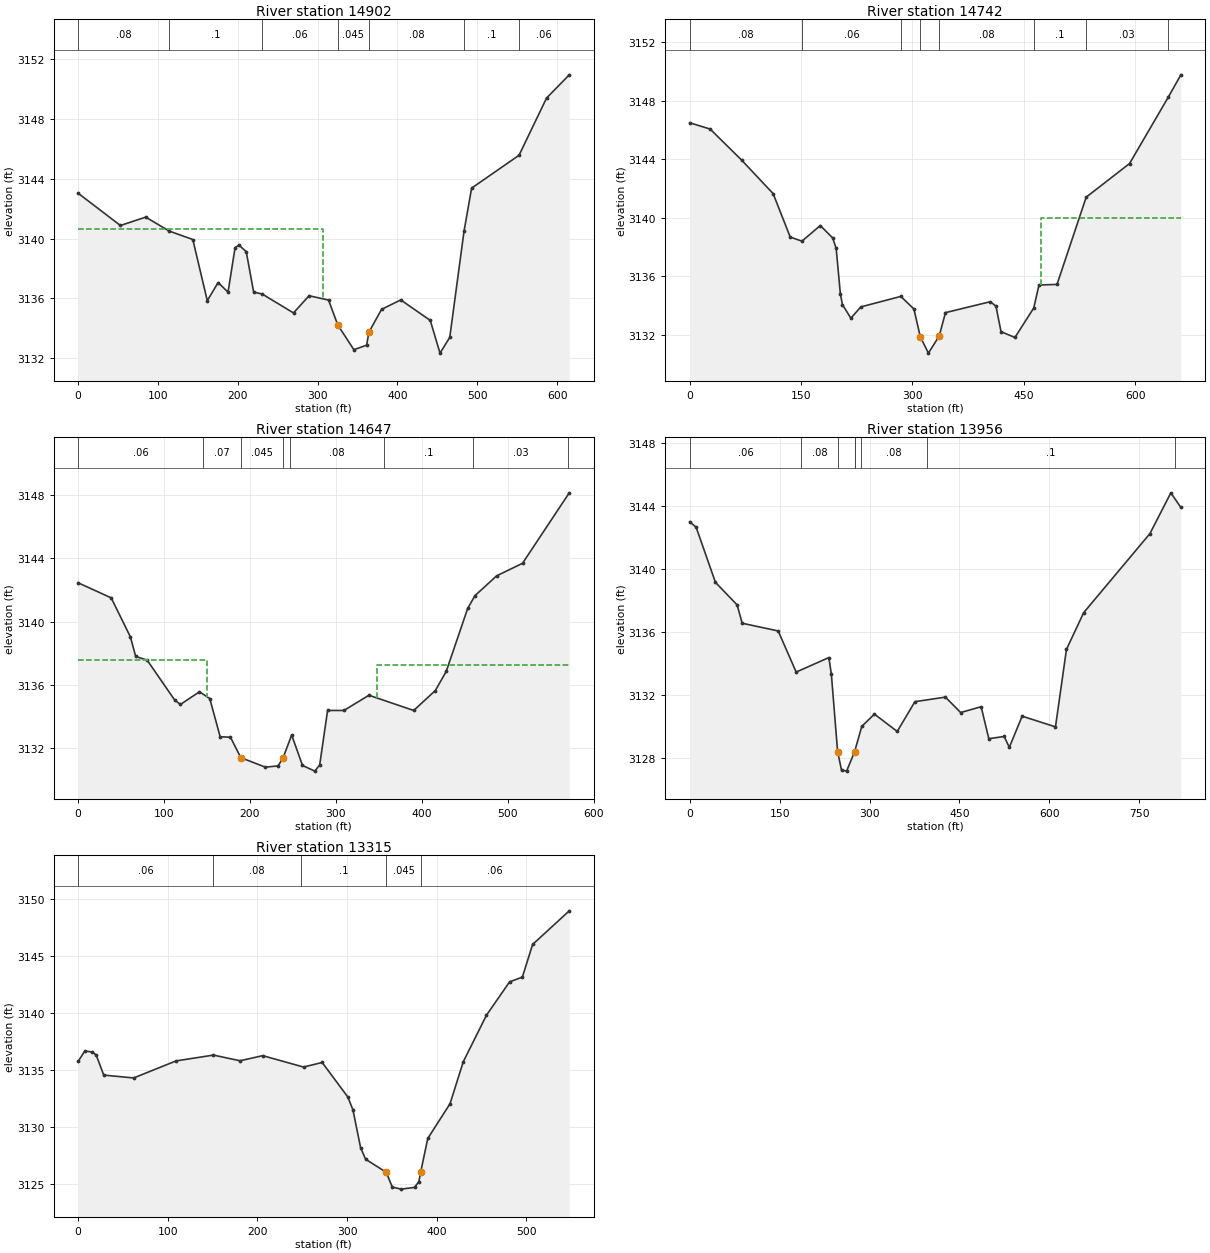
Type RM Length L Ch R = 1 ,14902   ,163.1,160.6,157.5
XS GIS Cut Line= 5
2204085.44651652 473609.635871432204243.55031912473694.024282896
2204306.06120558473801.6253787482204423.12464409473936.502818773
2204536.36710288474006.125498375
#Sta/Elev= 30
       0 3143.04      53 3140.88    84.7 3141.44     114 3140.51   143.7 3139.94
   161.8 3135.85   175.4 3137.06   187.8 3136.42   196.6 3139.39   201.4 3139.57
   210.6 3139.13   219.9 3136.42   230.4  3136.3   269.8 3135.03   289.3 3136.18
   313.7 3135.89   325.2 3134.23   345.4 3132.57   361.3 3132.87   364.4 3133.76
   380.1 3135.27   404.1  3135.9   441.1 3134.53   453.3 3132.34   465.5 3133.39
   483.4  3140.5   492.9 3143.38   552.3 3145.58   586.8 3149.41   615.2 3150.96
#Mann= 7 ,-1,0
       0     .08       0     114      .1       0   230.4     .06       0
   325.2    .045       0   364.4     .08       0   483.4      .1       0
   552.3     .06       0
#XS Ineff= 2 , 0
           306.9 3140.62
Permanent Ineff=
       F       F
Bank Sta=325.2,364.4
XS Rating Curve= 0 ,0
Exp/Cntr(USF)=0,0
Exp/Cntr=0.3,0.1

Type RM Length L Ch R = 1 ,14742   ,107.1,94.6,93.9
XS GIS Cut Line= 4
2203982.54633809473711.9330866142204109.37935658473844.403515938
2204331.90698411474046.0998616122204502.45817611 474096.17934154
#Sta/Elev= 30
       0  3146.5    27.5 3146.07    69.9 3143.95   112.4 3141.65   135.4 3138.68
   151.2  3138.4   175.9 3139.47   192.6 3138.62   197.3  3137.9   202.9 3134.81
   205.7 3134.06   217.1 3133.13   230.4  3133.9   284.3 3134.62     302 3133.76
   310.5 3131.87   321.5 3130.74     336 3131.91   344.5 3133.51   404.9 3134.26
   412.5 3133.95   419.3 3132.21     438 3131.81   463.4 3133.83   470.4  3135.4
   494.7 3135.44     534 3141.41   592.4 3143.71   644.3 3148.23   661.5 3149.78
#Mann= 8 ,-1,0
       0     .08       0   151.2     .06       0   284.3     .08       0
   310.5    .045       0     336     .08       0   463.4      .1       0
     534     .03       0   644.3     .06       0
#XS Ineff= 2 , 0
                           473.3            3140
Permanent Ineff=
       F       F
Bank Sta=310.5,336
XS Rating Curve= 0 ,0
Exp/Cntr(USF)=0,0
Exp/Cntr=0.3,0.1

Type RM Length L Ch R = 1 ,14647   ,687,690.9,661.2
XS GIS Cut Line= 6
2203998.53238455473892.734512109 2204082.0439301473998.890877351
2204142.90957018474003.1603500082204221.25322791 474064.37593766
2204315.36689683 474062.00971688 2204488.7328184474117.005878223
#Sta/Elev= 30
       0 3142.45    38.5  3141.5    60.9 3139.03      67  3137.8    80.3 3137.57
   112.5 3135.04   119.1 3134.77   141.2 3135.57   153.2 3135.14   165.3 3132.73
   177.3  3132.7   189.3 3131.41     218 3130.81   232.6 3130.89   238.3 3131.37
   248.5 3132.84   261.1 3130.92   275.4 3130.56   281.1 3130.95   290.3 3134.39
   309.3 3134.39   338.4 3135.35   390.5 3134.39   415.7 3135.65   428.3 3136.85
   453.3 3140.83   461.8 3141.64     487 3142.89   517.1 3143.68   571.5 3148.13
#Mann= 8 ,-1,0
       0     .06       0  145.07     .07       0   189.3    .045       0
   238.3     .07       0  246.08     .08       0  355.51      .1       0
  459.65     .03       0  569.65     .06       0
#XS Ineff= 2 , 0
          150.32 3137.55  347.37         3137.23
Permanent Ineff=
       F       F
Bank Sta=189.3,238.3
XS Rating Curve= 0 ,0
Exp/Cntr(USF)=0,0
Exp/Cntr=0.3,0.1

Type RM Length L Ch R = 1 ,13956   ,607.6,641.6,666.3
XS GIS Cut Line= 4
2203709.49751459474447.2702082192203854.77178819474463.250194849
2204131.94391407474369.403424399  2204487.848099474234.907658796
#Sta/Elev= 30
       0    3143    10.7 3142.66    42.9 3139.16    79.2 3137.72    87.5 3136.56
   147.6 3136.07   177.6 3133.46   232.1 3134.38   236.3 3133.32   246.7 3128.41
   253.2 3127.24   261.7 3127.17   275.1 3128.41     287 3130.01   308.1 3130.79
   346.1 3129.69   375.7 3131.58   426.5 3131.87   451.9 3130.89   486.1 3131.26
   498.9 3129.23   524.5 3129.37   533.1 3128.68   554.5 3130.66   610.1 3129.98
   628.4  3134.9   657.1 3137.23   767.6 3142.25   802.5 3144.84   819.2 3143.91
#Mann= 8 ,-1,0
       0     .06       0  186.15     .08       0   246.7    .045       0
   275.1     .08       0  276.15     .06       0  286.15     .08       0
  396.15      .1       0  808.78     .06       0
Bank Sta=246.7,275.1
XS Rating Curve= 0 ,0
Exp/Cntr(USF)=0,0
Exp/Cntr=0.3,0.1

Type RM Length L Ch R = 1 ,13315   ,400.6,396.1,386.1
XS GIS Cut Line= 3
2203753.07420295474557.7518024522203970.12561455474631.036063519
2204227.63802236474818.761903132
#Sta/Elev= 30
       0 3135.74     7.5 3136.66    15.9 3136.57    20.2  3136.3    28.6 3134.54
      62 3134.29   109.3 3135.79     151  3136.3   180.6  3135.8   205.9 3136.25
   251.4 3135.25   272.2 3135.65   300.8 3132.62   306.5 3131.49   315.1 3128.15
   320.7 3127.14   343.7 3125.99   350.4 3124.69   360.3 3124.51   375.2 3124.66
   380.1 3125.18   382.1 3126.02     390 3128.97   414.8 3132.02   429.6 3135.72
   455.4  3139.8   481.2 3142.74   495.5 3143.16   506.9 3146.03   547.8 3148.99
#Mann= 5 ,-1,0
       0     .06       0     150     .08       0  249.09      .1       0
   343.7    .045       0   382.1     .06       0
Bank Sta=343.7,382.1
XS Rating Curve= 0 ,0
Exp/Cntr(USF)=0,0
Exp/Cntr=0.3,0.1