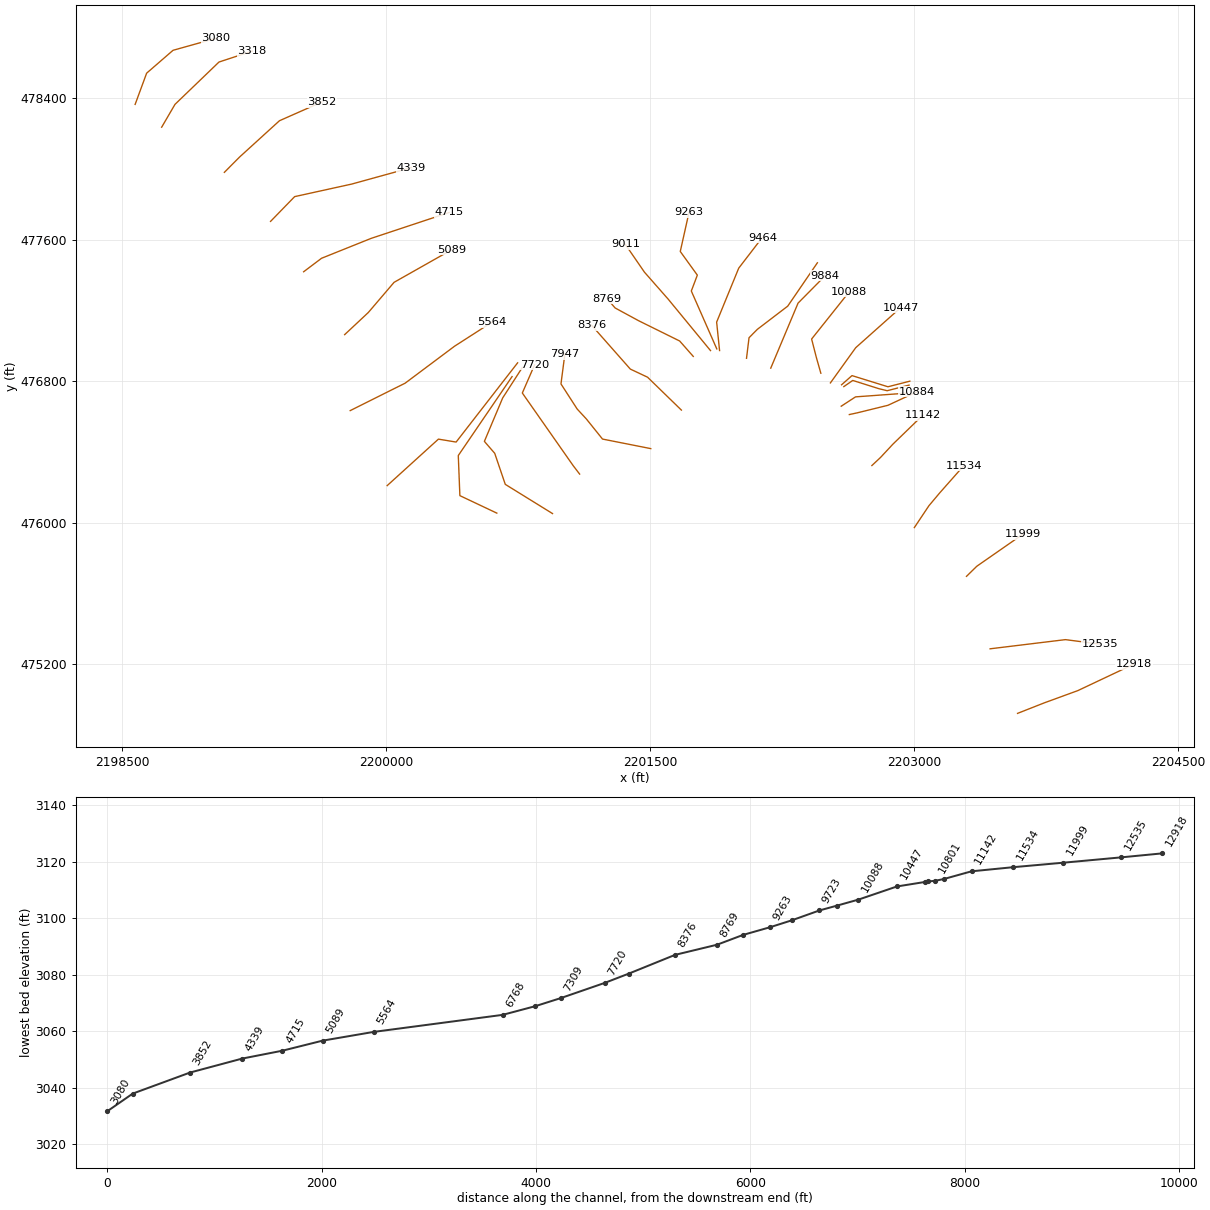
HEC-RAS study BIGLAURLCK.prj: BIGLAURLCK

--- BIGLAURLCK.g01 (geometry) --- (continued)

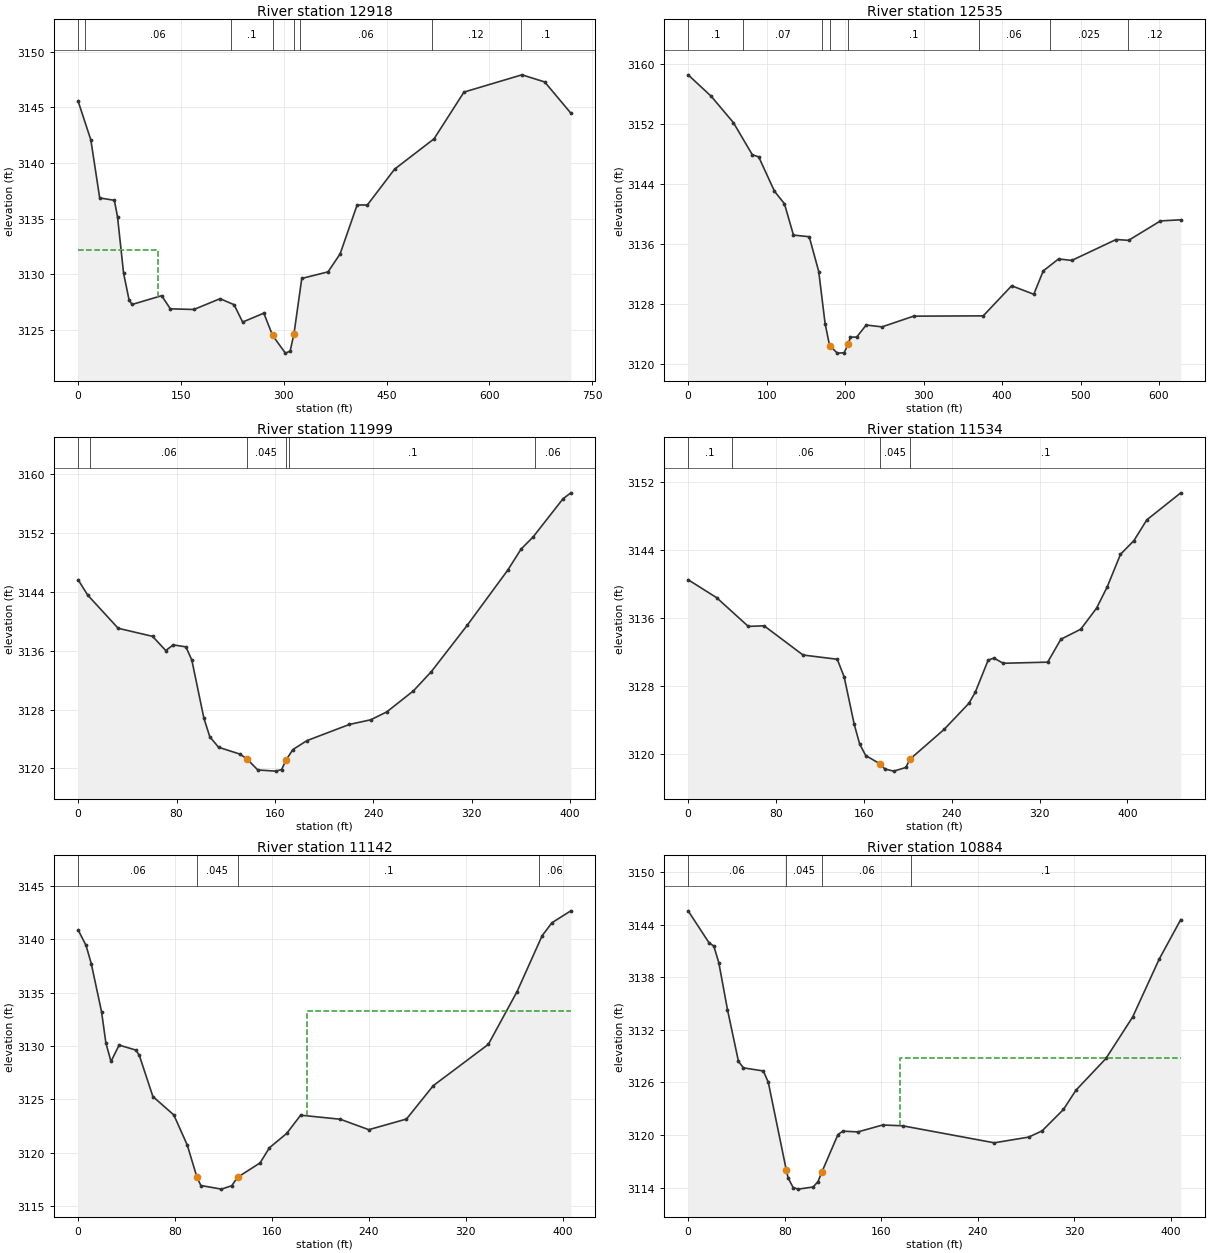
Type RM Length L Ch R = 1 ,12918   ,386.4,383.1,379.4
XS GIS Cut Line= 4
2203586.97686615474920.4541501512203738.87289105474980.017518001
2203929.34076444475049.2643297072204248.87313267475199.580398879
#Sta/Elev= 30
       0 3145.53    18.5 3142.06    31.4 3136.85    52.8 3136.64    57.4 3135.16
    66.3 3130.08    74.3 3127.68    78.6 3127.28   121.8 3128.07   134.5 3126.89
   168.8 3126.83   207.1  3127.8   227.5 3127.26     240  3125.7   270.9  3126.5
   283.7  3124.5   302.4 3122.91   309.3 3123.09   314.9 3124.64   326.3 3129.62
   364.6 3130.21   382.2 3131.82     407 3136.21     422 3136.22   461.8 3139.44
   519.3 3142.16     563 3146.36   647.5 3147.91   680.8 3147.27   718.9 3144.47
#Mann= 8 ,-1,0
       0      .1       0      10     .06       0  223.16      .1       0
   283.7    .045       0   314.9      .1       0  323.16     .06       0
  515.82     .12       0  645.82      .1       0
#XS Ineff= 2 , 0
          116.74 3132.13
Permanent Ineff=
       F       F
Bank Sta=283.7,314.9
XS Rating Curve= 0 ,0
Exp/Cntr(USF)=0,0
Exp/Cntr=0.3,0.1

Type RM Length L Ch R = 1 ,12535   ,524.1,536.2,546.7
XS GIS Cut Line= 3
 2203430.9508149475285.8179106042203858.81973779475337.708926161
2204053.89439875475312.421470111
#Sta/Elev= 30
       0 3158.61    29.4 3155.75    57.6 3152.25    81.8 3147.95    89.9 3147.67
     110 3143.09   122.7 3141.42   134.2 3137.24   154.3 3137.02   166.4 3132.38
   174.5 3125.45   180.2 3122.51   190.1  3121.5   198.7 3121.55   203.9 3122.67
   206.7 3123.62   214.8 3123.65   226.9 3125.25     247    3125   287.3 3126.43
     376 3126.47   412.2 3130.48   440.4 3129.35   452.5 3132.47     472 3134.06
   488.8 3133.86   545.3 3136.65   561.2 3136.54   601.8 3139.13   627.7 3139.28
#Mann= 8 ,-1,0
       0      .1       0      70     .07       0     170     .06       0
   180.2    .045       0   203.9      .1       0     370     .06       0
     461    .025       0     561     .12       0
Bank Sta=180.2,203.9
XS Rating Curve= 0 ,0
Exp/Cntr(USF)=0,0
Exp/Cntr=0.3,0.1

Type RM Length L Ch R = 1 ,11999   ,458.6,465.5,471.7
XS GIS Cut Line= 3
2203296.89889259475695.7778848572203355.26458992 475752.79078728
2203617.37441842475934.373090804
#Sta/Elev= 30
       0 3145.64     7.7 3143.57    32.5 3139.05    60.5 3137.95    71.2 3136.02
    77.3 3136.79    87.6 3136.52    92.4 3134.72   102.2 3126.82     107  3124.3
   114.1 3122.87   131.4 3121.94   137.1  3121.3     146 3119.78   160.6 3119.62
   165.4 3119.83   168.8 3121.07   174.5 3122.55     186 3123.77   220.5 3125.97
   237.8  3126.6   250.9 3127.68   272.5 3130.53   287.1 3133.15   316.3 3139.46
   349.2 3146.95   360.1 3149.83   369.8 3151.46   394.1 3156.65   400.5 3157.47
#Mann= 6 ,-1,0
       0      .1       0      10     .06       0   137.1    .045       0
   168.8     .06       0  171.59      .1       0  371.59     .06       0
Bank Sta=137.1,168.8
XS Rating Curve= 0 ,0
Exp/Cntr(USF)=0,0
Exp/Cntr=0.3,0.1

Type RM Length L Ch R = 1 ,11534   ,390.7,391.4,389
XS GIS Cut Line= 4
2203000.60346817475971.6692101382203083.69424561476095.695442271
2203145.30375518476168.6540720252203280.67729779476321.051113936
#Sta/Elev= 30
       0 3140.52    25.9 3138.42    54.8 3135.04    69.2 3135.11   104.6 3131.68
   135.8 3131.18   142.1  3129.1   151.2 3123.56   156.2 3121.22   161.7 3119.87
   174.8 3118.89   179.1 3118.29   187.2 3118.04   198.3 3118.47   201.8 3119.42
     233 3122.93   255.7 3126.01   261.5 3127.32   273.2 3131.08   278.4 3131.32
   286.9 3130.71   327.4 3130.84   339.4 3133.53   357.5 3134.71   371.9 3137.18
   381.6 3139.68   393.7 3143.51   405.9 3145.11   417.7 3147.56   448.6 3150.73
#Mann= 4 ,-1,0
       0      .1       0      40     .06       0   174.8    .045       0
   201.8      .1       0
Bank Sta=174.8,201.8
XS Rating Curve= 0 ,0
Exp/Cntr(USF)=0,0
Exp/Cntr=0.3,0.1

Type RM Length L Ch R = 1 ,11142   ,275.4,258.5,245.5
XS GIS Cut Line= 4
2202759.43366892476322.6778459512202808.07275543476368.074326687
 2202879.4100823476444.2755622082203049.23857331476608.024981782
#Sta/Elev= 30
       0 3140.89     6.5 3139.44    10.8 3137.74    19.3 3133.22    22.9 3130.28
    27.1 3128.55    33.8 3130.09    47.6 3129.62    50.4 3129.15    61.7 3125.26
      79 3123.53    90.1  3120.7    98.13117.681   101.3 3116.91   118.3 3116.57
   126.8 3116.89   131.63117.676   150.2 3119.03   157.9 3120.45   172.2  3121.8
   183.7 3123.51   216.4 3123.13     240 3122.15   271.1 3123.15   293.2 3126.28
   338.7 3130.16   362.4 3135.11   383.1 3140.35   391.2 3141.57   406.8 3142.69
#Mann= 4 ,-1,0
       0     .06       0    98.1    .045       0   131.6      .1       0
  380.91     .06       0
#XS Ineff= 2 , 0
                          189.15         3133.29
Permanent Ineff=
       F       F
Bank Sta=98.1,131.6
XS Rating Curve= 0 ,0
Exp/Cntr(USF)=0,0
Exp/Cntr=0.3,0.1

Type RM Length L Ch R = 1 ,10884   ,86.9,82.6,78.6
XS GIS Cut Line= 4
2202631.35074113476611.2697592022202675.12628093476620.593246122
2202850.62697942476663.557591563 2203016.4067375476740.163519406
#Sta/Elev= 30
       0 3145.56    17.2 3141.94    21.3 3141.53    25.4 3139.65    32.6 3134.29
    41.7  3128.4    45.8 3127.66    62.3 3127.31    66.4 3126.02    81.33116.027
    82.9 3115.09      87 3114.02    91.1 3113.84   103.5 3114.08   107.6  3114.7
   110.8  3115.8   124.1 3120.06   128.2 3120.45   140.6 3120.36   161.1 3121.15
   177.6 3121.06   253.6 3119.12   282.1 3119.77   293.2 3120.48   310.9 3122.92
   321.3 3125.12   346.1 3128.73   368.2 3133.45   390.2 3140.05   408.1 3144.57
#Mann= 4 ,-1,0
       0     .06       0    81.3    .045       0   110.8     .06       0
  184.76      .1       0
#XS Ineff= 2 , 0
                          175.54         3128.78
Permanent Ineff=
       F       F
Bank Sta=81.3,110.8
XS Rating Curve= 0 ,0
Exp/Cntr(USF)=0,0
Exp/Cntr=0.3,0.1

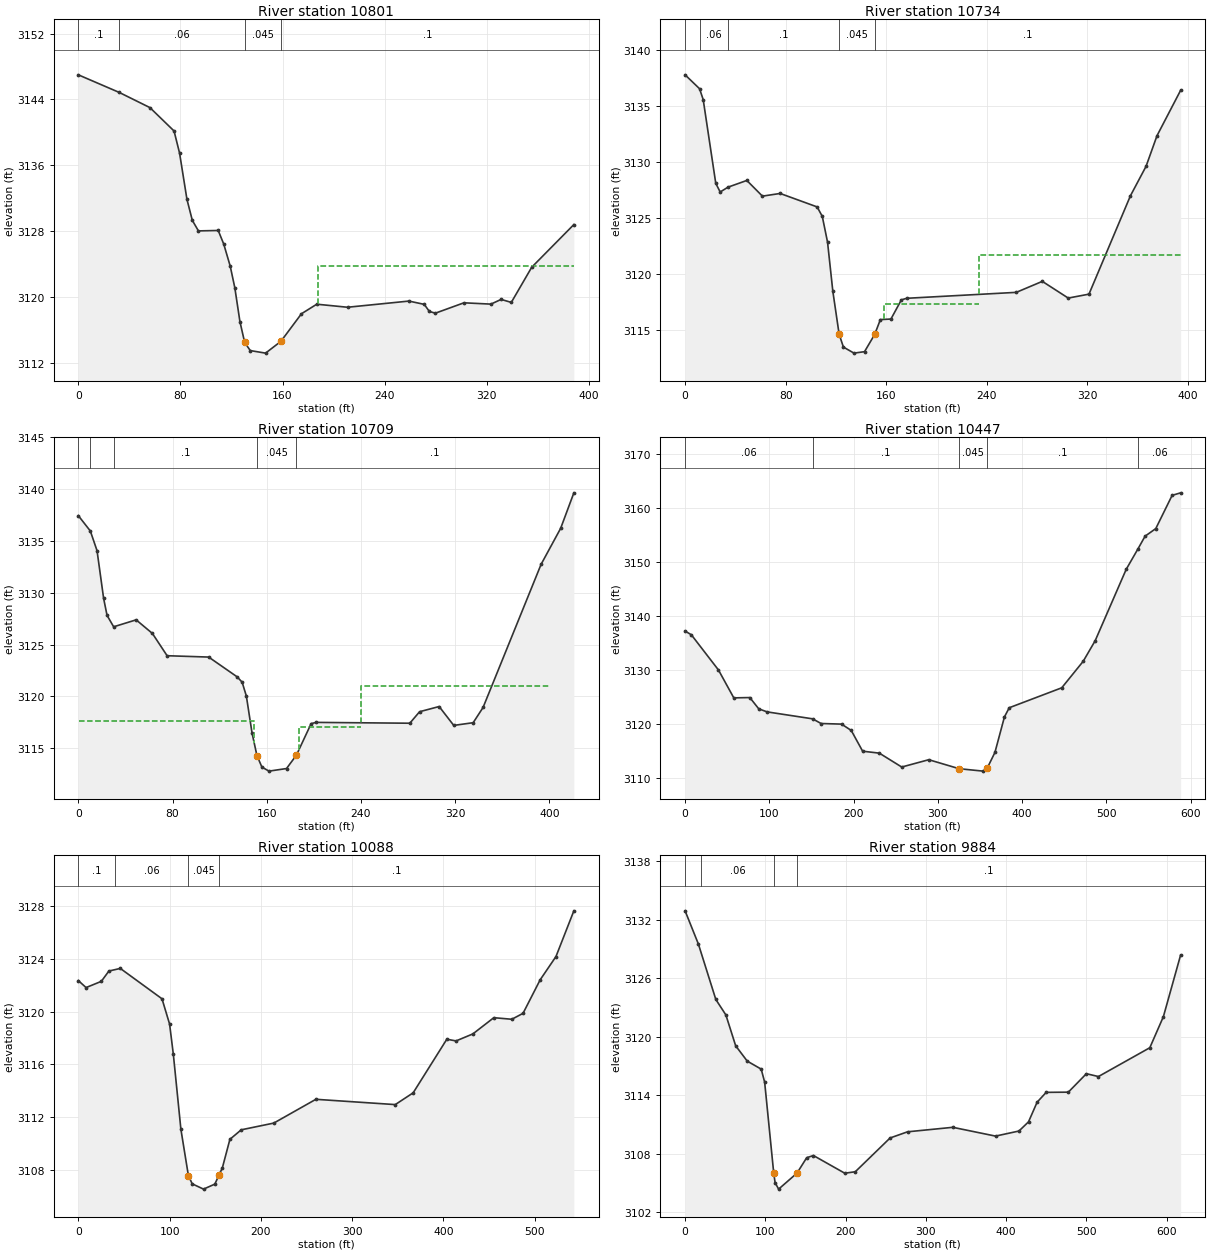
Type RM Length L Ch R = 1 ,10801   ,76.9,67.4,58.7
BEGIN DESCRIPTION:
xs 4
END DESCRIPTION:
XS GIS Cut Line= 3
2202585.25839017476658.4354558982202666.59497646 476711.25142102
2202957.08278463476732.377807069
#Sta/Elev= 30
       0 3146.99    32.1 3144.85    56.1 3143.01      75 3140.17    79.3  3137.5
    85.1 3131.87    89.3 3129.32    94.1 3128.04   109.6 3128.09   113.9 3126.45
     119 3123.76   122.6 3121.14   126.6 3117.03   130.33114.505   134.7 3113.51
   146.7  3113.2   158.7 3114.63   174.8 3117.98   186.8 3119.14   210.9 3118.77
     259 3119.52     271 3119.12     275 3118.26   279.7 3118.05   302.1 3119.31
   323.2 3119.15   331.2 3119.72   339.2 3119.36   355.2 3123.63   388.2 3128.81
#Mann= 4 ,-1,0
       0      .1       0    32.1     .06       0   130.3    .045       0
   158.7      .1       0
#XS Ineff= 2 , 0
                          187.94         3123.82
Permanent Ineff=
       F       F
Bank Sta=130.3,158.7
XS Rating Curve= 0 ,0
Exp/Cntr(USF)=0,0
Exp/Cntr=0.5,0.3

Type RM Length L Ch R = 1 ,10734   ,25.1,25.3,25.9
BEGIN DESCRIPTION:
xs 3
END DESCRIPTION:
XS GIS Cut Line= 5
 2202600.0468604476769.3489826542202650.75018692476804.207519635
2202798.63488926476757.7294703272202846.16925787   476746.109958
2202970.81493556476777.799537074
#Sta/Elev= 30
       0 3137.79    11.5 3136.55    14.4 3135.58    24.4 3128.11    27.9 3127.34
    34.1 3127.77    49.1 3128.37    61.5 3126.97    75.6 3127.21     105 3126.01
   109.1 3125.17   113.3 3122.86   117.5 3118.48   122.5 3114.66   125.9 3113.51
   134.3 3112.97   142.7  3113.1   150.8 3114.64   155.3 3115.96   163.7 3116.01
     172 3117.72   176.2 3117.86   263.4 3118.39   284.1 3119.37   304.7 3117.88
   321.2 3118.23   354.2 3127.01   366.6 3129.63   375.3 3132.36   394.1 3136.41
#Mann= 5 ,-1,0
       0      .1       0    11.5     .06       0    34.1      .1       0
   122.5    .045       0   150.8      .1       0
#XS Ineff= 3 ,-1
       0   115.5  3118.9   157.8     234 3117.36     234     400 3121.72
Permanent Ineff=
       F       F       F
Bank Sta=122.5,150.8
XS Rating Curve= 0 ,0
Exp/Cntr(USF)=0,0
Exp/Cntr=0.5,0.3

Type RM Length L Ch R = 1 ,10709   ,231.8,261.6,286.9
BEGIN DESCRIPTION:
xs 2
END DESCRIPTION:
XS GIS Cut Line= 4
2202587.25137146476779.7187956662202646.43772842476831.548259125
 2202850.6986439476768.4120457762202975.02325845476800.042860015
#Sta/Elev= 30
       0 3137.44    10.2 3135.96    15.9 3134.06    21.5 3129.45    24.4 3127.82
      30 3126.72    49.1 3127.39    62.9 3126.08    75.4 3123.93   110.7  3123.8
   134.9 3121.89   139.1 3121.38   142.7 3120.04   147.5 3116.49   151.7 3114.29
   155.9 3113.19   161.9  3112.8   176.8 3113.05   185.2 3114.34   197.7 3117.38
   201.9  3117.5   281.5 3117.42   289.8 3118.53   306.4 3119.03   318.8 3117.21
   335.3 3117.47   343.7 3118.94     393 3132.75   409.6 3136.22   420.8 3139.64
#Mann= 5 ,-1,0
       0      .1       0    10.2     .06       0      30      .1       0
   151.7    .045       0   185.2      .1       0
#XS Ineff= 3 ,-1
     .28  149.28  3117.6   187.2     240  3117.1     240     400    3121
Permanent Ineff=
       F       F       F
Bank Sta=151.7,185.2
XS Rating Curve= 0 ,0
Exp/Cntr(USF)=0,0
Exp/Cntr=0.5,0.3

Type RM Length L Ch R = 1 ,10447   ,325.3,359,384.6
XS GIS Cut Line= 3
2202523.83444081476790.2848537132202667.51676055 476989.42736016
 2202923.7472336 477216.81026998
#Sta/Elev= 30
       0 3137.21     7.4 3136.53    39.6 3129.99    57.8 3124.81    76.8 3124.87
    87.4 3122.78    97.3 3122.21   151.3 3120.92   161.4 3120.05   185.7 3119.94
   197.2 3118.76   210.7 3114.91   230.5 3114.55   257.1 3111.97   289.2 3113.33
   325.2 3111.66   353.7 3111.21   358.8 3111.84   367.7 3114.68     379 3121.28
   384.7 3122.98     447 3126.68   472.5 3131.61   486.7 3135.43   523.5 3148.68
   537.7 3152.54   545.9 3154.83   558.6 3156.24     578 3162.41   588.1 3162.88
#Mann= 5 ,-1,0
       0     .06       0   151.3      .1       0   325.2    .045       0
   358.8      .1       0   537.7     .06       0
Bank Sta=325.2,358.8
XS Rating Curve= 0 ,0
Exp/Cntr(USF)=0,0
Exp/Cntr=0.3,0.1

Type RM Length L Ch R = 1 ,10088   ,220,203.7,186.8
XS GIS Cut Line= 4
2202469.45418987 476844.990783672202443.78706913476934.825706233
2202417.05048504477038.5636525272202630.94315781477305.929493491
#Sta/Elev= 30
       0 3122.35     8.5 3121.82    25.2 3122.29    33.5 3123.07      46 3123.27
    91.7 3120.97     100 3119.06   104.1 3116.78   112.4 3111.09   120.6 3107.59
   124.8 3106.96   137.2 3106.56   149.6 3106.94   154.13107.616   157.8 3108.16
   166.1 3110.33   178.5 3111.05   214.2 3111.56   260.3 3113.36   347.3 3112.96
   366.9 3113.85   403.8 3117.91   413.9 3117.78   432.3 3118.31   455.3 3119.54
     475 3119.42   487.3 3119.87   506.1 3122.41   523.4 3124.17     543 3127.63
#Mann= 4 ,-1,0
       0      .1       0      40     .06       0   120.6    .045       0
   154.1      .1       0
Bank Sta=120.6,154.1
XS Rating Curve= 0 ,0
Exp/Cntr(USF)=0,0
Exp/Cntr=0.3,0.1

Type RM Length L Ch R = 1 ,9884    ,173.4,161.7,147.8
XS GIS Cut Line= 3
2202184.97693508476873.8662944942202340.04912284 477241.76169166
2202493.78371136477396.443760179
#Sta/Elev= 30
       0 3132.89    16.6 3129.48    38.3 3123.81    50.8 3122.23      63 3119.07
    77.4  3117.5    94.8 3116.68    99.1 3115.35  110.44 3106.01   112.1 3105.06
   116.5 3104.39   139.43106.029   151.5 3107.61   159.9 3107.83   198.9 3106.02
     212 3106.17   255.4 3109.63   277.1 3110.26   333.5 3110.72   386.7 3109.82
   415.9 3110.34   427.8 3111.28   438.5 3113.29   449.8  3114.3   477.4 3114.32
   499.9 3116.21   514.9 3115.92   578.9 3118.87   595.8 3122.05   617.3 3128.37
#Mann= 4 ,-1,0
       0      .1       0      20     .06       0  110.44    .045       0
   139.4      .1       0
Bank Sta=110.44,139.4
XS Rating Curve= 0 ,0
Exp/Cntr(USF)=0,0
Exp/Cntr=0.3,0.1

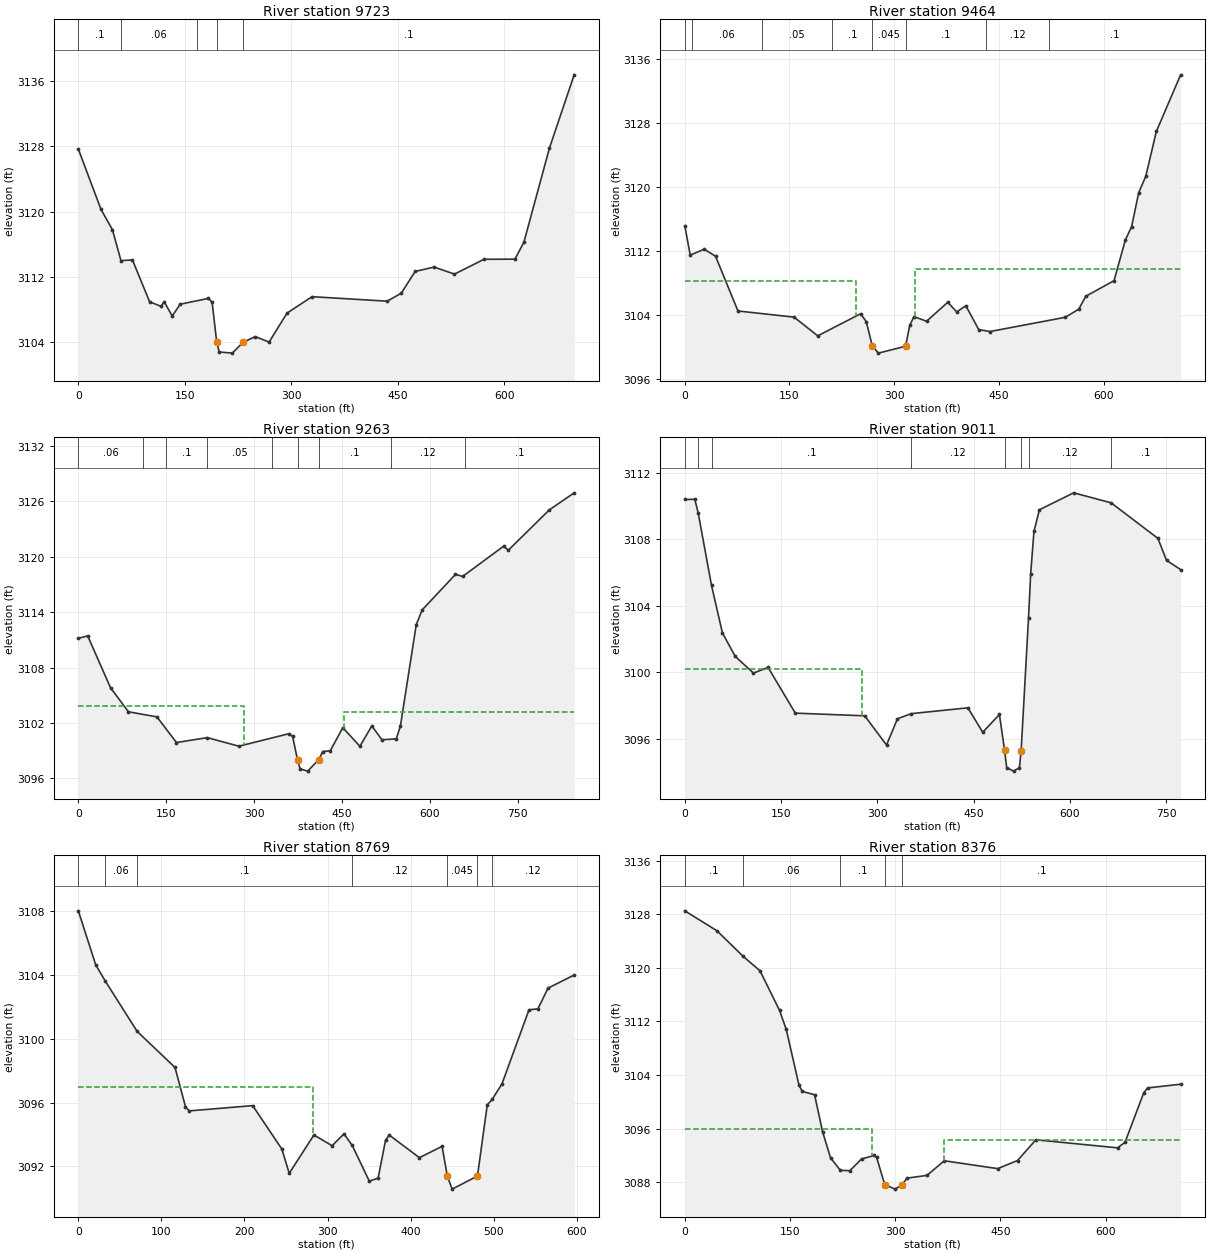
Type RM Length L Ch R = 1 ,9723    ,242.6,259,275.1
XS GIS Cut Line= 5
2202047.22217333476929.5647000492202061.53615107477045.865769151
2202108.85453105477093.4417486862202281.30318837477224.543067121
2202449.80279715477469.917359567
#Sta/Elev= 30
       0 3127.65    31.9 3120.27      48  3117.8    60.1    3114    76.2  3114.1
   100.4 3108.98   116.5 3108.42   120.9 3108.98   132.3 3107.24   143.6 3108.68
   183.3 3109.39   188.5 3108.93     195 3104.02   198.5 3102.84   216.9  3102.7
   232.1 3104.02   249.3 3104.72   268.8 3104.05     294 3107.59   329.3  3109.6
   435.1 3109.05   455.1 3110.03   474.5 3112.68   501.2 3113.22     530 3112.36
   571.5 3114.17   615.2 3114.19   627.8 3116.26   663.7 3127.74   698.6 3136.72
#Mann= 5 ,-1,0
       0      .1       0      60     .06       0  167.18      .1       0
     195    .045       0   232.1      .1       0
Bank Sta=195,232.1
XS Rating Curve= 0 ,0
Exp/Cntr(USF)=0,0
Exp/Cntr=0.3,0.1

Type RM Length L Ch R = 1 ,9464    ,200.9,201.1,201.7
XS GIS Cut Line= 4
2201894.15528515476973.4339390892201877.48360973477134.162532312
2202003.06032655477439.6651598182202136.62079988477612.737585183
#Sta/Elev= 30
       0 3115.12     7.8 3111.45    27.9 3112.18      44 3111.31    76.2 3104.46
   156.6 3103.69   190.5 3101.35   251.8 3104.11     260 3103.14   268.6 3100.12
   277.3 3099.19   316.4 3100.05   322.3 3102.65   328.4 3103.75   346.5 3103.18
   376.8 3105.55   389.7 3104.34   402.7 3105.12   421.2 3102.13   437.3 3101.89
   545.1 3103.67   564.5 3104.68   574.6  3106.3   615.1 3108.25   631.2 3113.31
   640.3 3115.02   650.4 3119.25   660.5 3121.28   675.7 3126.91   710.5 3133.99
#Mann= 8 ,-1,0
       0      .1       0      10     .06       0     110     .05       0
  211.59      .1       0   268.6    .045       0   316.4      .1       0
  431.59     .12       0   521.9      .1       0
#XS Ineff= 2 , 0
          245.78 3108.24  329.79         3109.76
Permanent Ineff=
       F       F
Bank Sta=268.6,316.4
XS Rating Curve= 0 ,0
Exp/Cntr(USF)=0,0
Exp/Cntr=0.3,0.1

Type RM Length L Ch R = 1 ,9263    ,226.4,252,278.3
XS GIS Cut Line= 5
2201878.37243639476982.6200708682201733.66339553477310.207346946
2201767.88622318 477400.042269512201670.91347697477533.882466779
2201720.50561892477754.796823226
#Sta/Elev= 30
       0 3111.16    15.9 3111.43    54.9 3105.81    85.5  3103.2   134.1 3102.65
   167.4 3099.87     220  3100.4   273.9 3099.47   358.9 3100.82   365.6 3100.53
   374.1 3097.94   378.4 3097.01   391.3 3096.77   409.93098.003     417 3098.89
   429.8 3098.98   451.2 3101.48   480.4 3099.46   500.7 3101.67   517.9 3100.17
   542.4 3100.26   549.4 3101.63   576.5 3112.64   586.6 3114.24   643.4 3118.09
   655.7 3117.87   725.4 3121.14   733.6 3120.71   803.3 3125.07   845.9 3126.93
#Mann= 9 ,-1,0
       0     .06       0     110     .05       0     150      .1       0
     220     .05       0     330      .1       0   374.1    .045       0
   409.9      .1       0  534.26     .12       0  659.54      .1       0
#XS Ineff= 2 , 0
          283.38 3103.84  452.96         3103.22
Permanent Ineff=
       F       F
Bank Sta=374.1,409.9
XS Rating Curve= 0 ,0
Exp/Cntr(USF)=0,0
Exp/Cntr=0.3,0.1

Type RM Length L Ch R = 1 ,9011    ,231.9,241.8,250.1
XS GIS Cut Line= 4
2201842.60625883476973.1384607342201601.82341015477264.654821224
2201467.25527083477417.0572922672201358.62797764 477574.32367196
#Sta/Elev= 30
       0 3110.39    15.6  3110.4    20.8 3109.59    41.6 3105.22    58.6 3102.36
    78.5 3100.95   106.9 3099.94   129.8 3100.28   172.2 3097.53   280.3 3097.37
   314.3 3095.61   331.3 3097.19   352.8  3097.5     441 3097.85   464.2 3096.38
   490.2 3097.45   498.1 3095.33   501.5 3094.25   512.2 3094.04   521.3 3094.25
     524 3095.25   535.5 3103.25   538.9 3105.92     544 3108.47   552.5 3109.77
   605.9 3110.79   664.1 3110.19   737.1 3108.05   750.5 3106.73   772.5 3106.17
#Mann= 8 ,-1,0
       0      .1       0    20.8     .06       0    41.6      .1       0
   352.8     .12       0   498.1    .045       0     524      .1       0
   535.5     .12       0   664.1      .1       0
#XS Ineff= 2 , 0
          276.28 3100.17
Permanent Ineff=
       F       F
Bank Sta=498.1,524
XS Rating Curve= 0 ,0
Exp/Cntr(USF)=0,0
Exp/Cntr=0.3,0.1

Type RM Length L Ch R = 1 ,8769    ,384,392.3,399.8
XS GIS Cut Line= 5
2201744.67923251476940.1948573412201667.53114896477027.326810518
 2201433.3640248477142.5951235742201300.85084601477214.297460042
 2201255.4696204477266.032057241
#Sta/Elev= 30
       0 3108.01    20.9 3104.63    32.2 3103.63    70.8 3100.46   116.4  3098.2
     129 3095.74   133.5 3095.48   209.9 3095.81     245 3093.09   253.9 3091.57
   283.6 3093.97   305.5  3093.3   319.8 3094.04   329.7 3093.32   350.3 3091.08
   360.9 3091.27   369.8 3093.63   374.2 3093.97   410.6 3092.55   437.9 3093.26
  444.16 3091.41     450 3090.58   480.5  3091.4   492.3 3095.86   498.2  3096.2
     510 3097.17   542.5 3101.81   553.2 3101.87   565.5 3103.17   596.9 3103.99
#Mann= 7 ,-1,0
       0      .1       0    32.2     .06       0    70.8      .1       0
   329.7     .12       0  444.16    .045       0   480.5      .1       0
   498.2     .12       0
#XS Ineff= 2 , 0
          282.75    3097
Permanent Ineff=
       F       F
Bank Sta=444.16,480.5
XS Rating Curve= 0 ,0
Exp/Cntr(USF)=0,0
Exp/Cntr=0.3,0.1

Type RM Length L Ch R = 1 ,8376    ,443.3,429.8,421.6
XS GIS Cut Line= 4
2201677.17641393 476636.499578052201485.18554278476822.490734478
2201387.19020229476868.4885473582201167.20066243477116.476755929
#Sta/Elev= 30
       0  3128.5    45.9 3125.52    83.2 3121.71   107.2 3119.56   135.1 3113.65
   144.7  3110.8   162.9 3102.47   167.7 3101.55   185.1 3101.06   196.4 3095.57
   207.9 3091.64   221.8 3089.79   235.3 3089.72     252 3091.48   270.1    3092
   273.6  3091.7   285.1 3087.65   300.2 3086.98  309.91 3087.66     317 3088.62
   345.3 3089.03   370.1 3091.21   446.2 3090.04   474.5 3091.25   500.7 3094.34
   617.1 3093.14   627.8 3093.97   654.5 3101.35   659.9 3102.08   707.1 3102.63
#Mann= 5 ,-1,0
       0      .1       0    83.2     .06       0   221.8      .1       0
   285.1    .045       0  309.91      .1       0
#XS Ineff= 2 , 0
             267 3095.91  369.13         3094.32
Permanent Ineff=
       F       F
Bank Sta=285.1,309.91
XS Rating Curve= 0 ,0
Exp/Cntr(USF)=0,0
Exp/Cntr=0.3,0.1

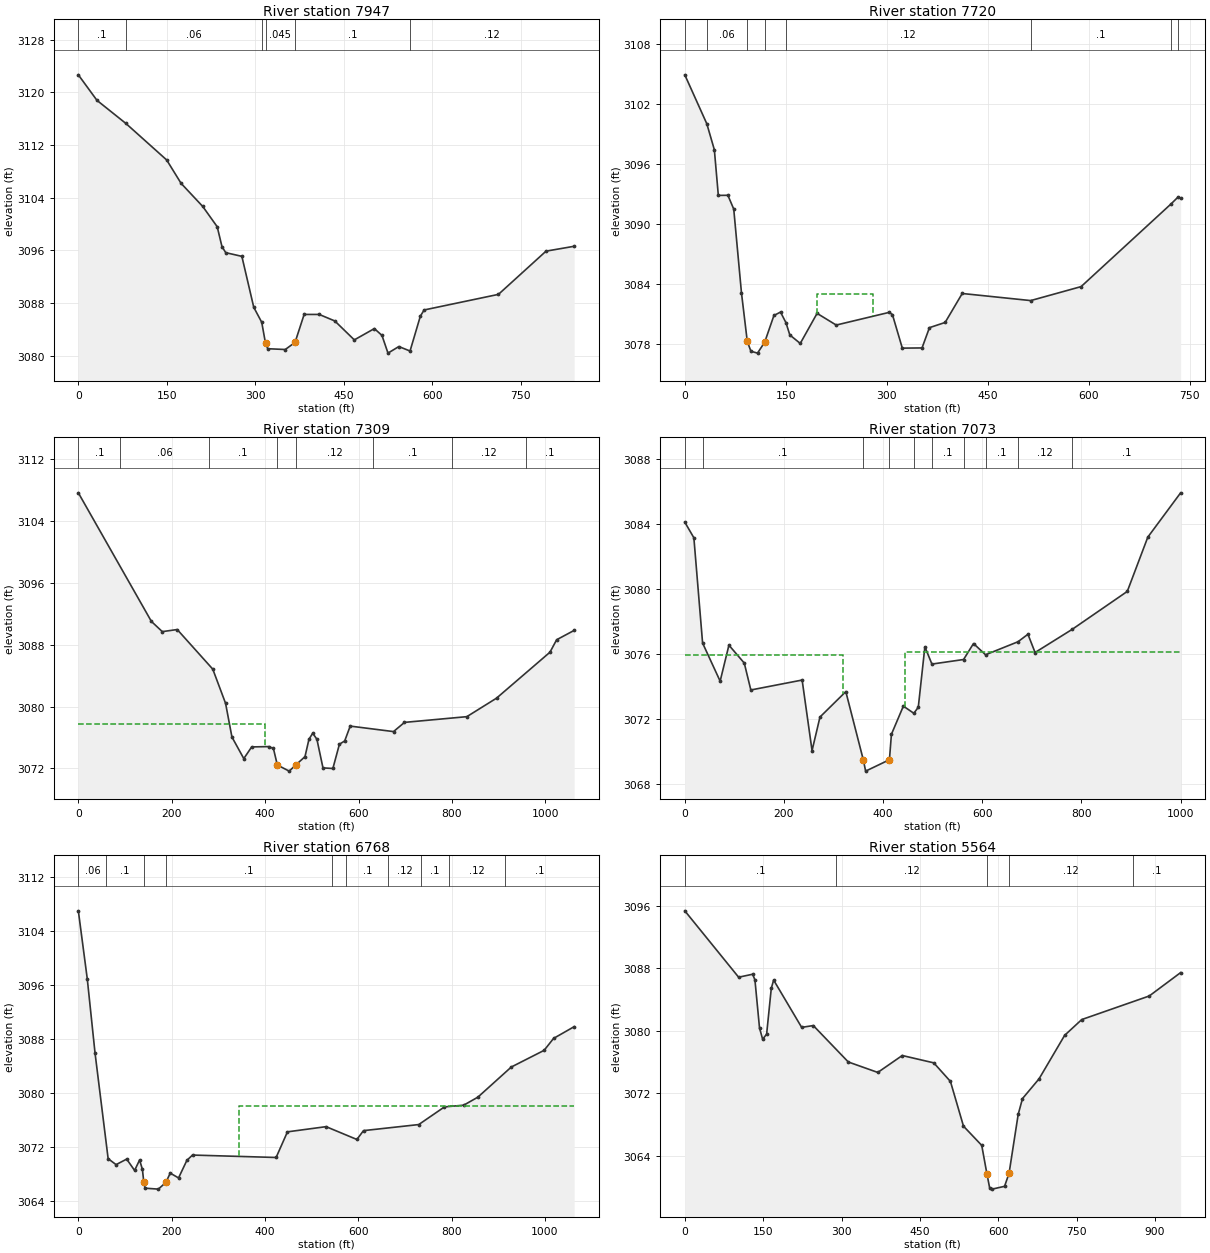
Type RM Length L Ch R = 1 ,7947    ,224.2,226.7,225.6
XS GIS Cut Line= 6
2201503.18468695476418.5099430972201229.19771457476472.507375608
2201137.20208881476586.5019553542201085.20456121476642.499292773
2200993.20893545476784.4925412292201015.20788944476952.484553487
#Sta/Elev= 30
       0 3122.67    31.6 3118.79    80.5 3115.29   149.8 3109.73   174.3 3106.17
     211 3102.66   235.5 3099.58   243.6 3096.55     250 3095.64   277.3 3095.08
   297.5 3087.33     311 3085.06   317.4 3081.87   321.2 3081.04   350.9 3080.92
   367.5    3082   382.9 3086.25   408.5 3086.25   434.9 3085.26     468 3082.38
     502  3084.1   514.9 3083.06   525.1 3080.37   543.5 3081.37   562.5 3080.69
     580 3085.99   586.4 3086.93   712.4  3089.3   793.1 3095.87   840.8 3096.61
#Mann= 6 ,-1,0
       0      .1       0    80.5     .06       0     311      .1       0
   317.4    .045       0   367.5      .1       0   562.5     .12       0
Bank Sta=317.4,367.5
XS Rating Curve= 0 ,0
Exp/Cntr(USF)=0,0
Exp/Cntr=0.3,0.1

Type RM Length L Ch R = 1 ,7720    ,419.8,410.7,411.5
XS GIS Cut Line= 4
2201099.21755371476274.3498748632201063.18860074476321.187513718
2200773.69234834476733.0236005842200843.25338205 476892.47822641
#Sta/Elev= 30
       0 3104.91    32.7 3100.01    43.9 3097.41    49.8 3092.84      64 3092.85
    72.7 3091.47    84.2 3083.07    92.8 3078.23    98.2 3077.24     108 3077.05
   118.7 3078.15   132.4 3080.82   142.2 3081.16   150.3 3080.09     156 3078.87
   171.5 3078.02   196.5 3081.03   224.9 3079.86   303.6 3081.13   308.4 3080.91
   323.1 3077.55   352.4 3077.57   363.4  3079.6   386.7 3080.12   412.1 3083.02
   513.8 3082.31   588.7 3083.71   722.5    3092   732.9 3092.69   736.5 3092.55
#Mann= 8 ,-1,0
       0      .1       0    32.7     .06       0    92.8    .045       0
   118.7     .06       0   150.3     .12       0   513.8      .1       0
   722.5     .12       0   732.9      .1       0
#XS Ineff= 1 ,-1
   196.2   279.5    3083
Permanent Ineff=
       F
Bank Sta=92.8,118.7
XS Rating Curve= 0 ,0
Exp/Cntr(USF)=0,0
Exp/Cntr=0.3,0.1

Type RM Length L Ch R = 1 ,7309    ,242.9,236.3,223.3
XS GIS Cut Line= 6
2200945.16972239476050.9599394772200676.81973004 476216.27297777
2200616.84519636476391.894066713 2200558.1282244476459.428573528
2200662.22642197476705.5287592762200773.12752463 476876.71200961
#Sta/Elev= 30
       0 3107.63   156.4 3091.01   179.7 3089.69   211.7 3089.96   287.8 3084.84
   315.2 3080.42   328.8 3076.07   354.2 3073.28   371.1 3074.79   407.8 3074.83
   417.6 3074.59     426 3072.45   451.4 3071.66  466.07 3072.49   485.2 3073.53
   493.7 3075.78   501.8 3076.56   510.7 3075.78   523.7 3072.08   544.9    3072
   558.9 3075.14   570.2 3075.56     582 3077.48   674.7 3076.77   698.2 3077.96
   831.7  3078.7   895.2 3081.09  1009.6 3087.03  1023.9 3088.64  1061.4 3089.85
#Mann= 8 ,-1,0
       0      .1       0      90     .06       0     280      .1       0
     426    .045       0  466.07     .12       0  630.25      .1       0
  800.25     .12       0  957.46      .1       0
#XS Ineff= 2 , 0
           400.5 3077.75
Permanent Ineff=
       F       F
Bank Sta=426,466.07
XS Rating Curve= 0 ,0
Exp/Cntr(USF)=0,0
Exp/Cntr=0.3,0.1

Type RM Length L Ch R = 1 ,7073    ,331.4,304.8,272.4
XS GIS Cut Line= 4
 2200628.6959294476053.541866157 2200418.9338199476152.372090825
2200409.85757478476379.278218889 2200715.4244939476826.031173254
#Sta/Elev= 30
       0  3084.1    18.3 3083.14    35.9 3076.68    71.3 3074.34      89 3076.55
     120 3075.45   133.2  3073.8   236.7 3074.41   256.7 3070.08   272.7 3072.14
   324.8  3073.7  360.03 3069.52   364.8 3068.82   412.8 3069.52   416.8 3071.08
   440.9 3072.81     462 3072.37     471 3072.74   484.3 3076.45   498.5 3075.39
   562.3 3075.67   582.4 3076.65   606.7 3075.96   672.1 3076.76   692.2 3077.22
   706.6  3076.1   781.4 3077.52   892.6 3079.85     934 3083.18  1000.2  3085.9
#Mann= 10 ,-1,0
       0     .06       0    35.9      .1       0  360.03    .045       0
   412.8      .1       0     462     .12       0   498.5      .1       0
   562.3     .12       0   606.7      .1       0   672.1     .12       0
   781.4      .1       0
#XS Ineff= 2 , 0
          319.77 3075.96  444.63         3076.15
Permanent Ineff=
       F       F
Bank Sta=360.03,412.8
XS Rating Curve= 0 ,0
Exp/Cntr(USF)=0,0
Exp/Cntr=0.3,0.1

Type RM Length L Ch R = 1 ,6768    ,1208.5,1204.4,1191.3
XS GIS Cut Line= 4
2200005.92112517 476209.145316122200296.99903692476472.147630473
2200397.58892785476455.556979825 2200746.9629671476903.925450115
#Sta/Elev= 30
       0 3106.99    19.2 3096.89    35.8 3085.91    63.9 3070.25    80.9 3069.37
   103.6 3070.19   120.6 3068.51   131.3 3070.06   137.3 3068.68   140.4 3066.73
   143.2 3065.88   171.5 3065.74  187.54 3066.73     197 3068.11   214.8  3067.4
   232.7 3070.01   244.7 3070.79   423.9 3070.43   448.2 3074.23     531    3075
     597  3073.1   611.2 3074.41   729.6 3075.31   784.8 3077.93   825.9 3078.18
   856.3 3079.37     928 3083.84   998.3 3086.31  1018.6 3088.08  1062.7 3089.82
#Mann= 10 ,-1,0
       0     .06       0      60      .1       0   140.4    .045       0
  187.54      .1       0  544.25     .12       0  574.25      .1       0
  664.25     .12       0  734.25      .1       0  794.25     .12       0
  914.25      .1       0
#XS Ineff= 2 , 0
                           344.7         3078.11
Permanent Ineff=
       F       F
Bank Sta=140.4,187.54
XS Rating Curve= 0 ,0
Exp/Cntr(USF)=0,0
Exp/Cntr=0.3,0.1

Type RM Length L Ch R = 1 ,5564    ,468.3,475,482.6
XS GIS Cut Line= 4
 2199795.9737001476633.5931013192200108.13869219476788.861489895
2200388.75545139476997.9253186872200599.48362228477132.819012017
#Sta/Elev= 30
       0 3095.38     103 3086.87   129.8 3087.25   134.2 3086.53     143 3080.35
     149 3078.91   156.6 3079.58   165.5 3085.44     170  3086.5   223.6 3080.44
   245.9 3080.67   312.9    3076   369.3 3074.66   416.1 3076.83   476.4 3075.89
   508.3 3073.51   533.3 3067.77   568.2 3065.31   578.1 3061.67   583.3 3059.88
   588.1  3059.7   611.9 3060.06   620.5 3061.73     638 3069.29   646.2 3071.31
   677.9 3073.84   726.9 3079.42   759.6 3081.44   888.7 3084.46   948.8 3087.46
#Mann= 5 ,-1,0
       0      .1       0     290     .12       0   578.1    .045       0
   620.5     .12       0  858.58      .1       0
Bank Sta=578.1,620.5
XS Rating Curve= 0 ,0
Exp/Cntr(USF)=0,0
Exp/Cntr=0.3,0.1

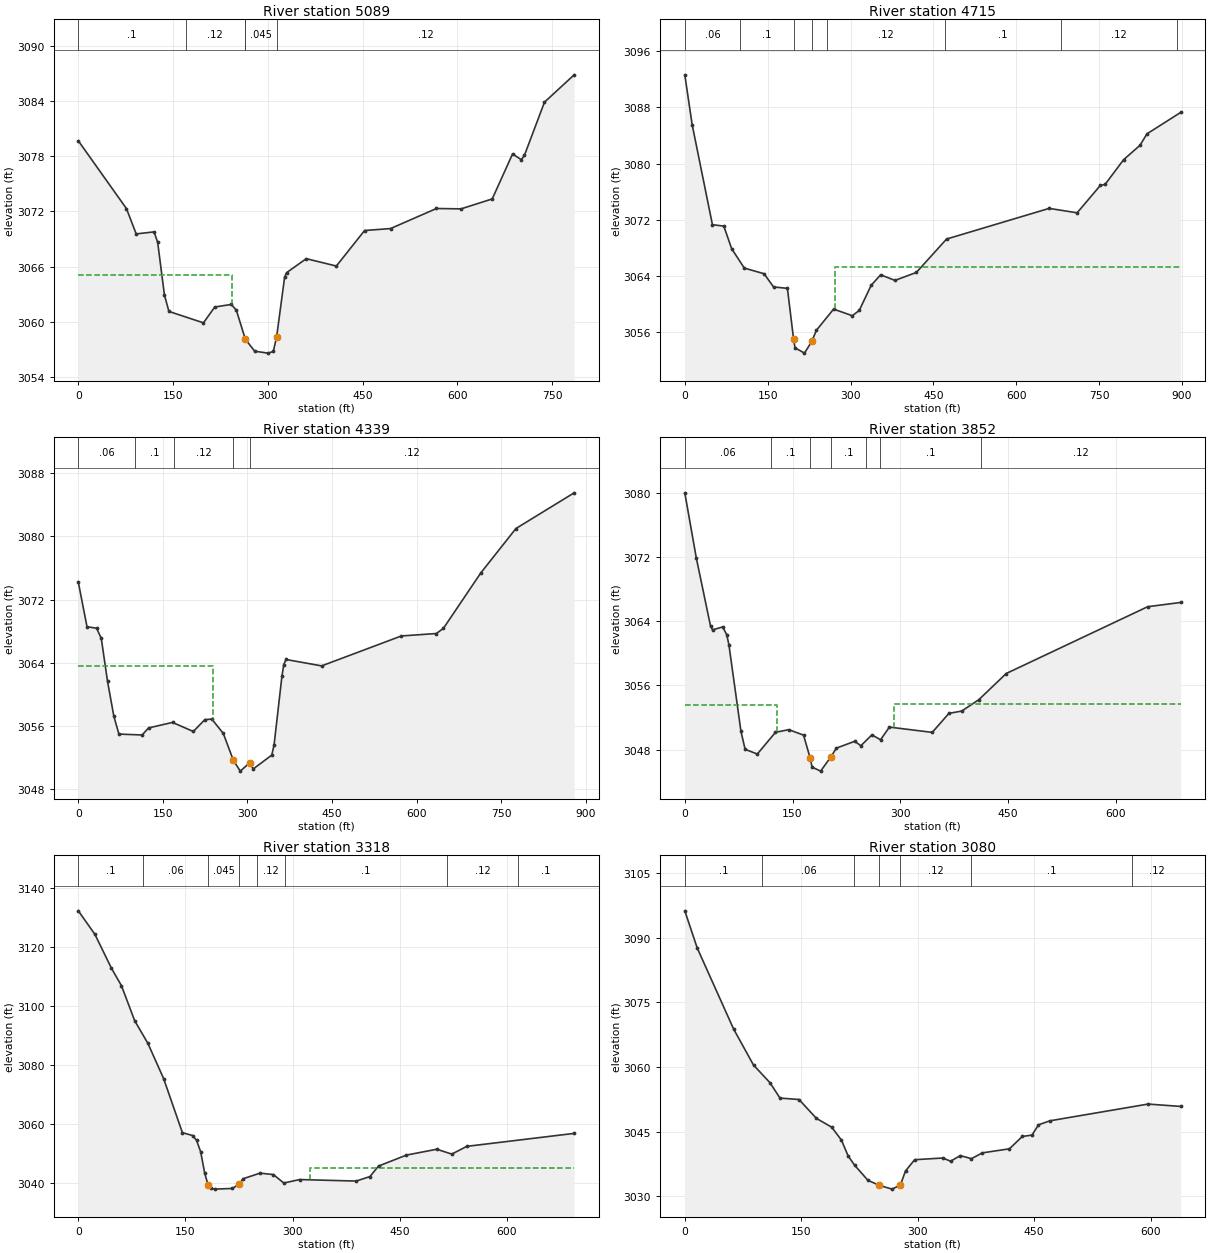
Type RM Length L Ch R = 1 ,5089    ,386.5,374,360.4
XS GIS Cut Line= 4
2199764.44753518477063.4191811632199898.68130124477188.500644996
2200045.11813695477359.3436199872200373.12617005477544.175571226
#Sta/Elev= 30
       0 3079.67    76.2 3072.31    91.6 3069.56   119.9 3069.78   125.6 3068.65
   136.3 3062.93   143.4 3061.14   198.1  3059.9     216 3061.62   242.3  3061.9
   250.3 3061.25   264.4 3058.12   279.2 3056.82   300.3 3056.61   308.7 3056.79
     3143058.398   326.6 3064.86   329.7 3065.35   360.9 3066.87   408.5 3066.07
   453.2 3069.93   494.3 3070.14     567 3072.32   605.9 3072.28   655.3 3073.36
   687.5 3078.25   701.3 3077.62   706.2 3078.08     738 3083.87     785 3086.84
#Mann= 5 ,-1,0
       0      .1       0     170     .12       0  263.48      .1       0
   264.4    .045       0     314     .12       0
#XS Ineff= 2 , 0
          242.93 3065.07
Permanent Ineff=
       F       F
Bank Sta=264.4,314
XS Rating Curve= 0 ,0
Exp/Cntr(USF)=0,0
Exp/Cntr=0.3,0.1

Type RM Length L Ch R = 1 ,4715    ,376.6,375.4,368
XS GIS Cut Line= 4
2199531.40809764477419.170664629 2199633.0326272477495.439849893
2199914.92028948477608.0647670542200358.01689652 477754.45646058
#Sta/Elev= 30
       0 3092.63    13.4 3085.51      50 3071.32    70.6 3071.12    84.8 3067.91
   107.7 3065.15   143.4 3064.35   160.6 3062.47   185.7 3062.27   196.9 3055.03
   199.4 3053.82   216.6 3053.06     230 3054.75   238.1  3056.3   269.3 3059.32
   303.2 3058.38   315.7 3059.13   337.2 3062.69   354.4  3064.2   380.3  3063.4
     419 3064.53   473.7 3069.28   659.4 3073.64     710 3073.01   752.1 3076.91
   760.5 3077.04   794.2 3080.57   823.7  3082.6   836.4 3084.24   897.3 3087.28
#Mann= 8 ,-1,0
       0     .06       0     100      .1       0   196.9    .045       0
     230      .1       0  257.06     .12       0  470.62      .1       0
  680.62     .12       0  890.62      .1       0
#XS Ineff= 2 , 0
                          271.04         3065.24
Permanent Ineff=
       F       F
Bank Sta=196.9,230
XS Rating Curve= 0 ,0
Exp/Cntr(USF)=0,0
Exp/Cntr=0.3,0.1

Type RM Length L Ch R = 1 ,4339    ,477.7,487.8,502.5
XS GIS Cut Line= 4
2199343.44163252477704.0803373792199480.29795753477844.245760684
2199804.37990046477915.2627990272200143.85041287 478008.55899239
#Sta/Elev= 30
       0 3074.19    15.4 3068.56    32.4 3068.37    40.7 3067.09    51.8 3061.64
      63 3057.23      72 3054.96   113.3 3054.85   124.5 3055.74   167.1 3056.44
     204 3055.29   224.4 3056.79   236.9 3056.86   257.2 3055.04     275 3051.65
   287.3 3050.27   304.1 3051.33   310.4 3050.55   343.2  3052.3   347.3 3053.59
   361.2 3062.27   364.5 3063.76   368.4 3064.41   431.7  3063.6   573.1 3067.39
   635.3  3067.7   647.8 3068.36   714.1 3075.38   776.4    3081   879.7 3085.52
#Mann= 5 ,-1,0
       0     .06       0     100      .1       0     170     .12       0
     275    .045       0   304.1     .12       0
#XS Ineff= 2 , 0
          239.32 3063.56
Permanent Ineff=
       F       F
Bank Sta=275,304.1
XS Rating Curve= 0 ,0
Exp/Cntr(USF)=0,0
Exp/Cntr=0.3,0.1

Type RM Length L Ch R = 1 ,3852    ,531.4,533.7,527.7
XS GIS Cut Line= 4
2199081.07563522477981.7001717392199167.42793488 478068.22234899
 2199394.0411402478273.6500600052199634.18831967478379.475020114
#Sta/Elev= 30
       0 3080.01      16  3071.9    35.8 3063.41    38.6 3062.92    52.7 3063.29
    58.4 3062.32    61.4 3061.08    78.2 3050.27      84 3048.03     101 3047.44
   126.3 3050.15   144.8 3050.48   165.4  3049.8   174.4 3046.99   177.3 3045.81
   189.2 3045.31   203.3 3047.08   211.2 3048.18   236.6 3049.03   245.2 3048.48
   260.6 3049.83   272.6 3049.22   284.9  3050.8   344.6 3050.14   367.8 3052.51
   385.7  3052.8   409.5 3054.22   447.6 3057.48   644.6 3065.81   690.5 3066.34
#Mann= 7 ,-1,0
       0     .06       0     120      .1       0   174.4    .045       0
   203.3      .1       0  252.24     .12       0  272.24      .1       0
  412.24     .12       0
#XS Ineff= 2 , 0
          128.17 3053.59  290.65         3053.69
Permanent Ineff=
       F       F
Bank Sta=174.4,203.3
XS Rating Curve= 0 ,0
Exp/Cntr(USF)=0,0
Exp/Cntr=0.3,0.1

Type RM Length L Ch R = 1 ,3318    ,239.7,237.4,235
XS GIS Cut Line= 4
2198724.87935839478237.1001337752198800.48348819478366.208724667
2199050.55868677478605.8156591172199238.98744104478667.462103418
#Sta/Elev= 30
       0 3132.35    23.3 3124.33    46.4 3112.84    60.4 3106.92    78.9 3095.05
    97.4 3087.35   119.4  3075.4   145.7 3057.04     160 3056.07   165.5 3054.44
   171.3 3050.53     177 3043.21   181.6 3039.35   185.4 3038.11   191.1 3037.87
   215.7  3038.1   225.1 3039.54   230.7 3041.39   254.4  3043.3   273.1 3042.81
   287.7 3039.94   309.8 3041.12   389.1 3040.61   408.3 3042.14   420.3  3045.7
   459.4 3049.43   501.9 3051.41   522.9 3049.76   543.9 3052.39   694.2 3056.79
#Mann= 8 ,-1,0
       0      .1       0      90     .06       0   181.6    .045       0
   225.1     .06       0  249.62     .12       0  289.62      .1       0
  515.95     .12       0  615.95      .1       0
#XS Ineff= 2 , 0
                          324.17         3045.01
Permanent Ineff=
       F       F
Bank Sta=181.6,225.1
XS Rating Curve= 0 ,0
Exp/Cntr(USF)=0,0
Exp/Cntr=0.3,0.1

Type RM Length L Ch R = 1 ,3080    ,204.5,206.6,209.4
XS GIS Cut Line= 4
2198574.18315447 478366.176123852198639.48769986  478542.7402651
2198789.44628558478672.1400124532199032.52431566478739.863244713
#Sta/Elev= 30
       0  3096.3      16 3087.66    62.9 3068.82    88.5 3060.46   109.8 3056.34
   122.6 3052.78   147.1 3052.45   169.5 3048.07   189.2 3046.02   201.8 3043.01
   210.3 3039.37   218.8 3037.17   235.8 3033.69     250 3032.53     267 3031.62
   277.7 3032.56   284.3 3035.84   296.1 3038.46   332.3 3038.85   342.4 3038.11
     355 3039.42   369.1 3038.69   383.3 3040.05   418.2 3040.99   434.8 3043.87
   447.3 3044.18   455.6 3046.57   470.6 3047.51   596.8 3051.39   638.7 3050.84
#Mann= 7 ,-1,0
       0      .1       0     100     .06       0  218.25     .12       0
     250    .045       0   277.7     .12       0  368.25      .1       0
  576.32     .12       0
Bank Sta=250,277.7
XS Rating Curve= 0 ,0
Exp/Cntr(USF)=0,0
Exp/Cntr=0.3,0.1