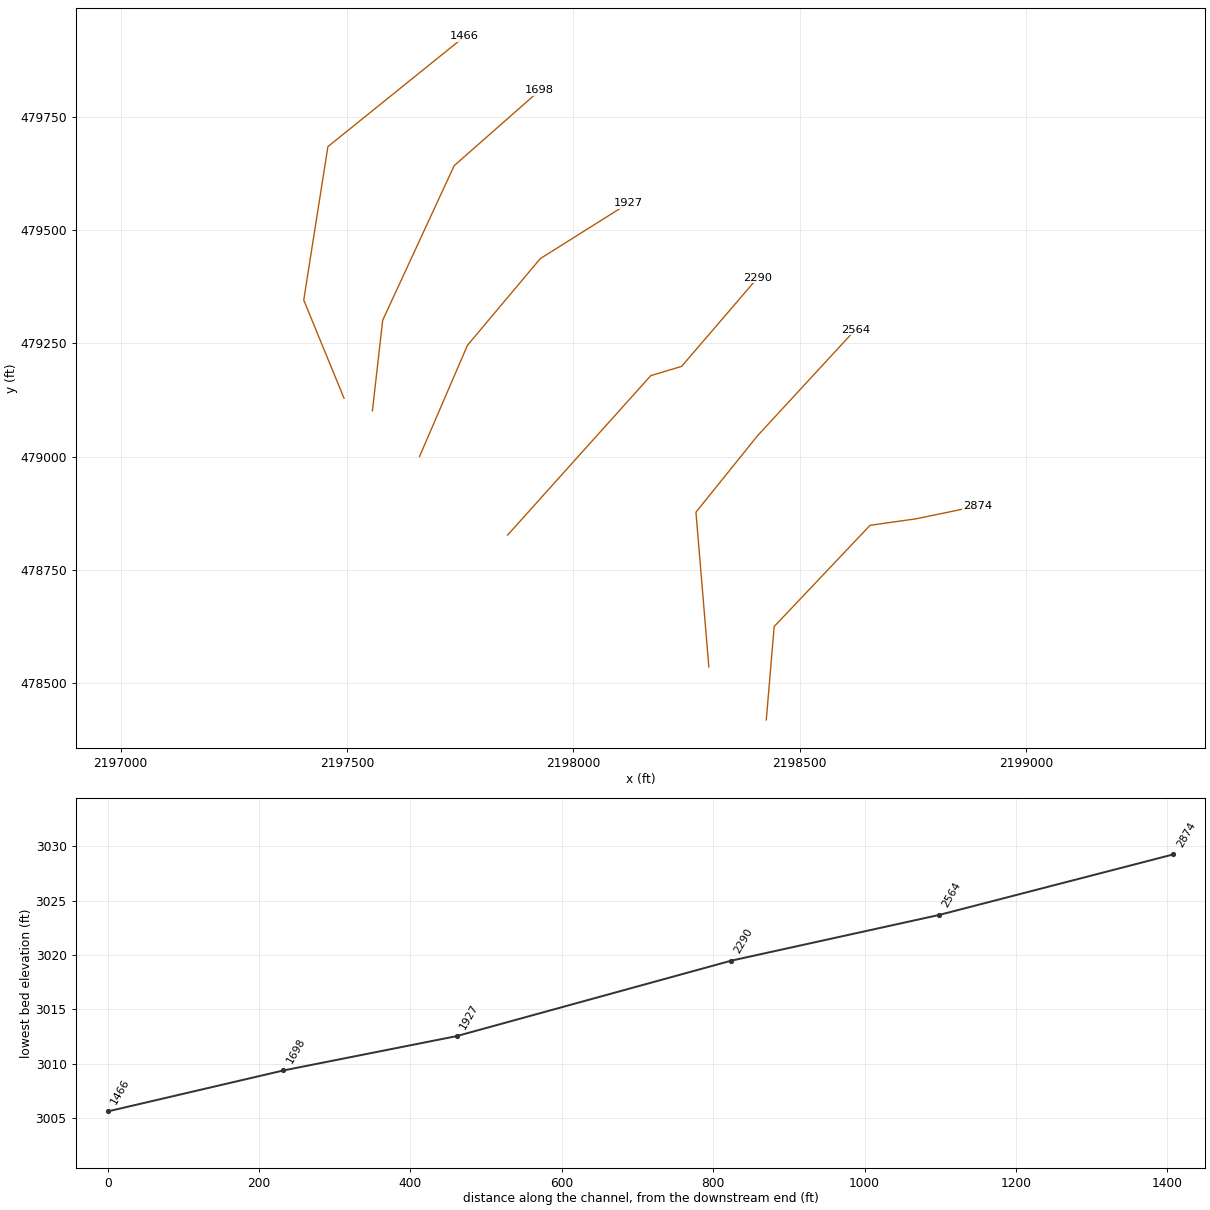
HEC-RAS study BIGLAURLCK.prj: BIGLAURLCK

--- BIGLAURLCK.g01 (geometry) --- (continued)

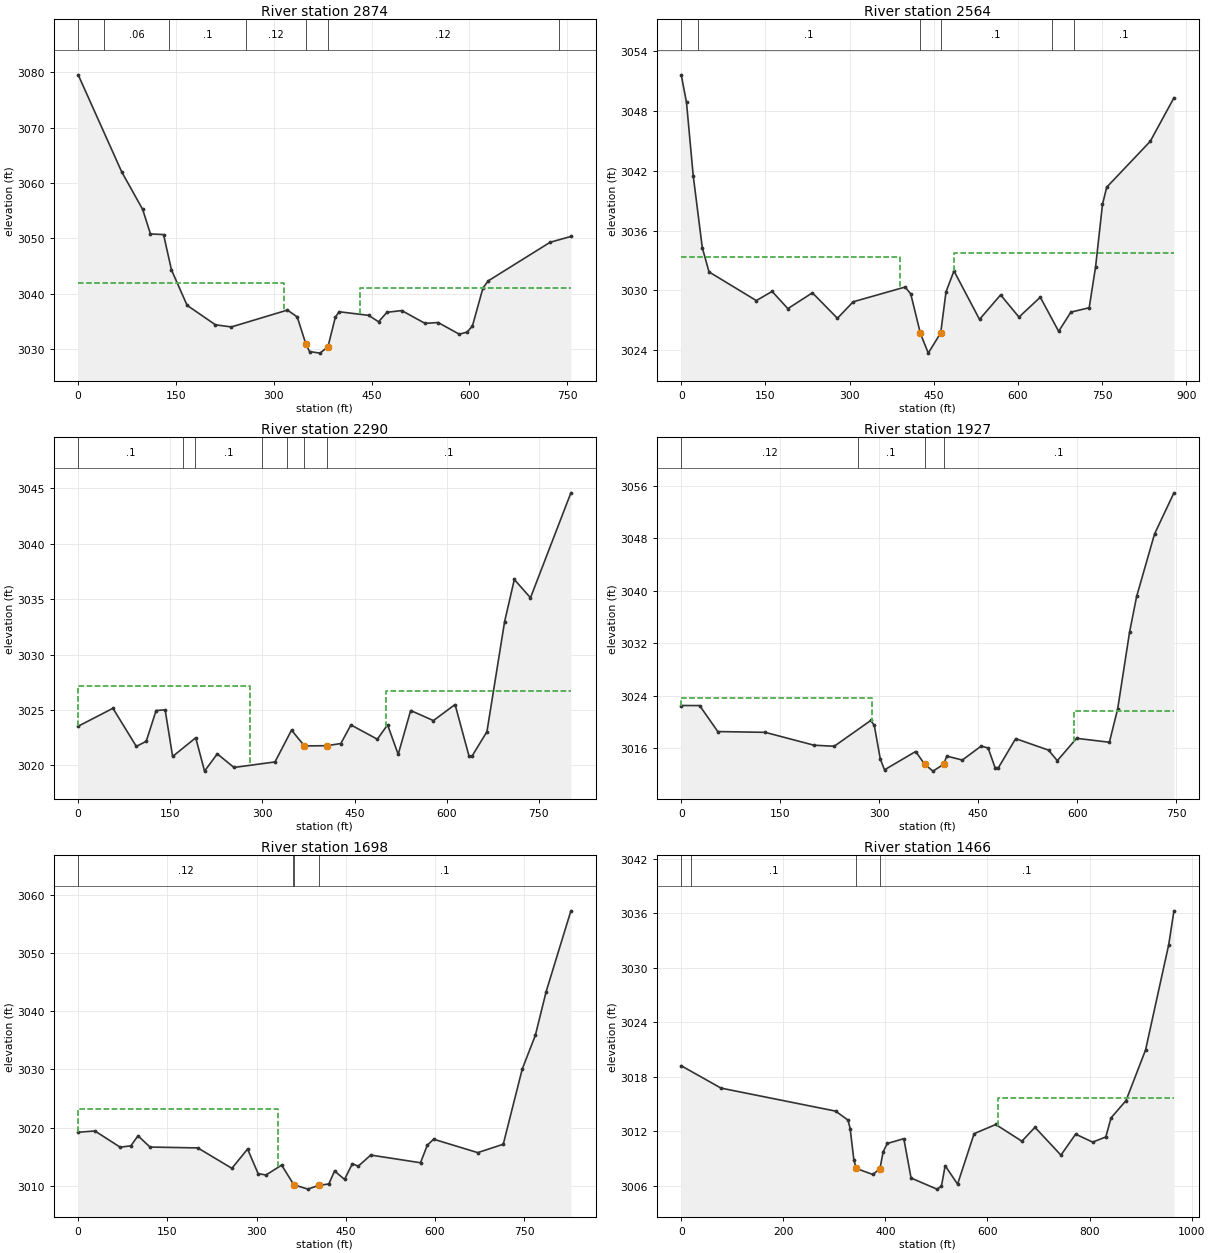
Type RM Length L Ch R = 1 ,2874    ,307.2,309.5,311.7
XS GIS Cut Line= 5
 2198425.9356346478418.6253637112198443.36976408478624.895433598
2198655.20318121478848.4293166662198756.15637198478862.639388093
2198892.26238129478890.802357865
#Sta/Elev= 30
       0 3079.53    66.8 3061.99    98.9 3055.22   110.9 3050.78     131 3050.66
   143.1 3044.29   167.1 3037.88   210.6 3034.36     235 3033.97     321 3037.02
   336.1 3035.78   349.2 3030.93   354.9 3029.53     371 3029.24   383.2 3030.39
   394.5 3035.72   400.2 3036.72   445.4 3036.07   460.9 3034.91   473.7 3036.62
   496.4 3036.93   532.1 3034.62   552.3 3034.77   584.6 3032.66   596.7 3033.04
   604.8 3034.13     621 3041.02   629.1  3042.3     724 3049.27   755.9 3050.32
#Mann= 7 ,-1,0
       0      .1       0      40     .06       0     140      .1       0
  257.01     .12       0   349.2    .045       0   383.2     .12       0
  736.92      .1       0
#XS Ineff= 2 , 0
          316.39 3041.86  432.23         3040.95
Permanent Ineff=
       F       F
Bank Sta=349.2,383.2
XS Rating Curve= 0 ,0
Exp/Cntr(USF)=0,0
Exp/Cntr=0.3,0.1

Type RM Length L Ch R = 1 ,2564    ,276.9,274.8,274
XS GIS Cut Line= 4
2198299.09805677478535.8477454022198270.65622126478877.407346532
2198406.85603748479046.4179980222198622.44125816479280.137945575
#Sta/Elev= 30
       0 3051.64     9.4 3048.86    21.4 3041.49    37.5 3034.29    49.5 3031.84
   133.8 3028.96   161.9 3029.88     190 3028.15   233.7 3029.74   278.3 3027.18
   306.4 3028.84     399 3030.32   408.9 3029.63   426.1 3025.66   440.1 3023.68
   462.33025.711   471.7 3029.83   485.9 3031.94   531.4 3027.07     569 3029.53
   601.7  3027.3   639.7  3029.3   672.4 3025.87   694.2  3027.8   726.8 3028.24
   738.2 3032.35   750.5 3038.62     758 3040.35   835.6 3044.96   877.8 3049.33
#Mann= 6 ,-1,0
       0     .06       0      30      .1       0   426.1    .045       0
   462.3      .1       0   659.8     .12       0   699.8      .1       0
#XS Ineff= 2 , 0
           389.3 3033.37   486.2         3033.76
Permanent Ineff=
       F       F
Bank Sta=426.1,462.3
XS Rating Curve= 0 ,0
Exp/Cntr(USF)=0,0
Exp/Cntr=0.3,0.1

Type RM Length L Ch R = 1 ,2290    ,358.8,363,361.6
XS GIS Cut Line= 4
2197854.66713617478826.7627444622198170.81752491479178.738684596
2198239.01751172479199.3313440642198407.06149892 479395.08294778
#Sta/Elev= 30
       0 3023.53    56.6 3025.15    94.7 3021.71   110.8 3022.17   126.9 3024.95
   141.6 3025.01   153.8  3020.8   191.4 3022.49   205.8 3019.48   226.5 3021.04
   253.7 3019.81   320.5 3020.31   347.4 3023.18   368.43021.753   404.93021.776
   427.7 3021.97   444.1 3023.65   487.1 3022.36   503.8 3023.66   521.1 3020.99
   541.4 3024.95   578.4 3024.04   613.7 3025.49   636.4 3020.84   641.7 3020.87
   665.6 3023.04   694.4 3032.98   710.2 3036.77   736.5 3035.12   802.3 3044.59
#Mann= 7 ,-1,0
       0      .1       0     170     .12       0     190      .1       0
     300     .12       0     340      .1       0   368.4    .045       0
   404.9      .1       0
#XS Ineff= 2 , 0
             280 3027.15  501.05         3026.68
Permanent Ineff=
       F       F
Bank Sta=368.4,404.9
XS Rating Curve= 0 ,0
Exp/Cntr(USF)=0,0
Exp/Cntr=0.3,0.1

Type RM Length L Ch R = 1 ,1927    ,220.6,228.7,236.2
XS GIS Cut Line= 4
 2197660.3558631479000.3981559792197766.02500369479245.737145187
2197926.97792952479437.2441204462198121.01519084479559.227485994
#Sta/Elev= 30
       0 3022.55    27.9 3022.54    55.4 3018.58   127.2 3018.46   201.2  3016.5
   231.8 3016.34   287.3 3020.28   292.5 3019.51   301.6  3014.4     308 3012.75
   355.2 3015.54  368.76 3013.61   381.4 3012.55  397.67  3013.6   402.3 3014.84
   425.9 3014.24   454.5 3016.37     465 3016.07   475.4  3013.1   480.6 3013.08
   506.7  3017.5   556.5 3015.75   569.8 3014.14     599 3017.55   648.7 3016.95
   661.3 3022.06   679.3 3033.75     690 3039.18   717.1 3048.69   746.5 3054.96
#Mann= 4 ,-1,0
       0     .12       0  267.13      .1       0  368.76    .045       0
  397.67      .1       0
#XS Ineff= 2 , 0
           288.9 3023.76  594.53         3021.76
Permanent Ineff=
       F       F
Bank Sta=368.76,397.67
XS Rating Curve= 0 ,0
Exp/Cntr(USF)=0,0
Exp/Cntr=0.3,0.1

Type RM Length L Ch R = 1 ,1698    ,224,232.1,240.3
XS GIS Cut Line= 4
2197556.21562074479101.154904803 2197578.9159552479301.153562289
2197736.79492594479642.5067861382197925.60275024479808.681642195
#Sta/Elev= 30
       0 3019.19    28.2  3019.4    70.6 3016.62    88.6 3016.85   100.7 3018.58
   120.8 3016.64   201.3 3016.49   258.6 3012.98     285  3016.3   302.7 3012.07
   315.9 3011.83   342.3 3013.53   362.7 3010.16   386.4  3009.4   404.4 3010.04
   421.7 3010.29   431.3 3012.52   448.1 3011.08   461.3 3013.78   471.1 3013.34
   492.2 3015.26   575.9 3013.94   587.3 3016.95   597.9 3017.99   672.2 3015.68
   715.1 3017.12   747.1 3030.08   769.1 3035.86   787.3 3043.39   828.9 3057.28
#Mann= 4 ,-1,0
       0     .12       0  361.28      .1       0   362.7    .045       0
   404.4      .1       0
#XS Ineff= 2 , 0
          336.96 3023.24
Permanent Ineff=
       F       F
Bank Sta=362.7,404.4
XS Rating Curve= 0 ,0
Exp/Cntr(USF)=0,0
Exp/Cntr=0.3,0.1

Type RM Length L Ch R = 1 ,1466    ,,,
XS GIS Cut Line= 4
2197493.50852575479129.0329909332197404.59400432479345.725930387
 2197457.9789195479684.5380195662197760.09334645479928.089779671
#Sta/Elev= 30
       0 3019.21      78 3016.75   302.5 3014.22   326.8 3013.23   330.9  3012.3
   338.3 3008.83     343 3007.91   375.4 3007.25   389.33007.888   395.6 3009.75
   403.7 3010.66   436.1 3011.19   450.3 3006.86   500.9 3005.64   509.7 3005.94
   517.1 3008.22   541.4 3006.19   573.8 3011.74   616.2 3012.75   667.4 3010.91
     693 3012.44   743.9 3009.38   772.7 3011.69   806.1 3010.81   831.8 3011.38
   842.1 3013.48   871.4 3015.38   909.7 3020.95   955.1 3032.54   965.3 3036.25
#Mann= 4 ,-1,0
       0     .12       0      20      .1       0     343    .045       0
   389.3      .1       0
#XS Ineff= 2 , 0
                          620.56         3015.65
Permanent Ineff=
       F       F
Bank Sta=343,389.3
XS Rating Curve= 0 ,0
Exp/Cntr(USF)=0,0
Exp/Cntr=0.3,0.1
LCMann Table=0

Chan Stop Cuts=-1
Use User Specified Reach Order=0
Composite Channel Slope=5